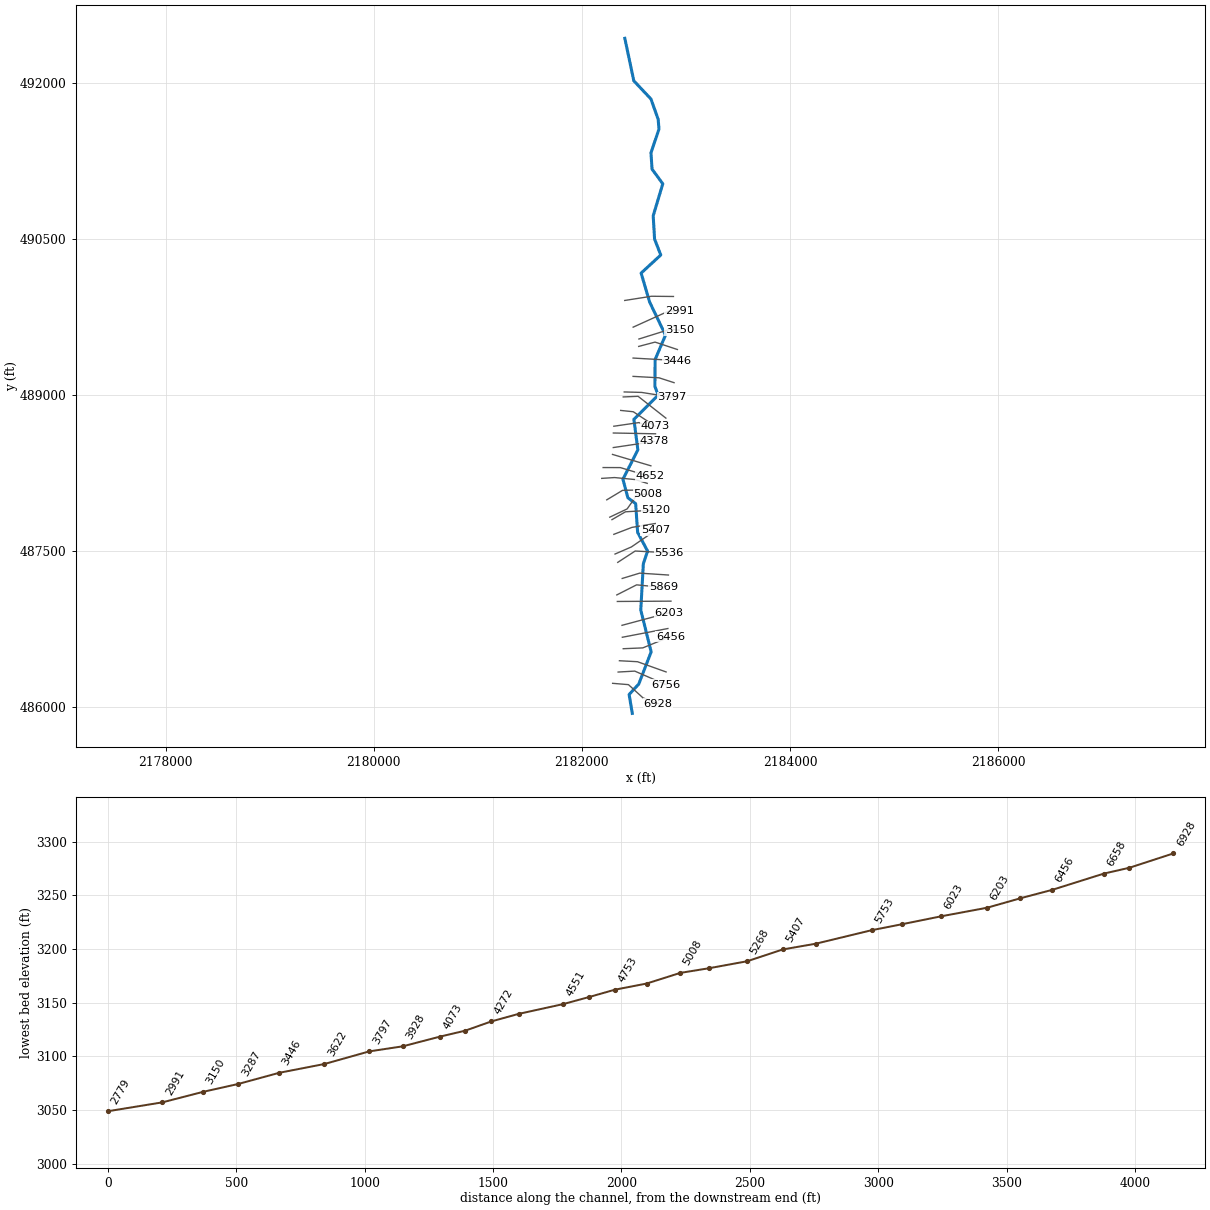
--- KENSCK.prj (project) ---

Proj Title=KENSCK
Current Plan=p01
Default Exp/Contr=0,0
English Units
Geom File=g01
Flow File=f01
Plan File=p01
Background Map Layer=Inundation Boundary (01pct Value_0)
Background Map Layer=Inundation Boundary (01pct Value_0)
BEGIN DESCRIPTION:
----------MODEL BY WOOD PLC 2021----------
Stream Name: Kens Creek
Flood Zone: Approximate
Pocahontas County, WV
HEC-RAS Version: RAS 6.1
Vertical Datum: NAVD88
Projection: NAD 1983 StatePlane West Virginia S FIPS 4702 (US Feet)
Terrain: 1-meter LIDAR (FEMA Region III 3DEP collected 2016-2018)
Land Use: 2019 NLCD
Hydrologic Method:
WV SIR2010-5033 regression equations
END DESCRIPTION:
DSS Export Rating Curves= 0
DSS Export Rating Curve Sorted= 0
DSS Export Volume Flow Curves= 0
DXF OffsetX= 0
DXF OffsetY= 0
DXF ScaleX= 0
DXF ScaleY= 0

--- KENSCK.p01 (plan) ---

Plan Title=Floodplain
Program Version=6.00
Short Identifier=Floodplain
Geom File=g01
Flow File=f01
Subcritical Flow
K Sum by GR= 0
Std Step Tol= 0.01
Critical Tol= 0.01
Num of Std Step Trials= 20
Max Error Tol= 0.3
Flow Tol Ratio= 0.001
Split Flow NTrial= 30
Split Flow Tol= 0.02
Split Flow Ratio= 0.02
Log Output Level= 0
Friction Slope Method= 1
Unsteady Friction Slope Method= 2
Unsteady Bridges Friction Slope Method= 1
Parabolic Critical Depth
Global Vel Dist= 0 , 0 , 0
Global Log Level= 0
CheckData=False
Encroach Param=-1 ,0,0, 0
Mapping Interval=1HOUR
Computation Time Step Use Courant=        0
Computation Time Step Use Time Series=    0
Computation Time Step Count To Double=0
Computation Time Step Max Doubling=0
Computation Time Step Max Halving=0
Computation Time Step Residence Courant=0
Run HTab= 0
Run UNet= 0
Run Sediment= 0
Run PostProcess= 0
Run WQNet= 0
Run RASMapper=-1
UNET Theta= 0
UNET Theta Warmup= 0
UNET ZTol= 0
UNET ZSATol= 0
UNET MxIter= 0
UNET Max Iter WO Improvement= 0
UNET MaxInSteps= 0
UNET DtIC= 0
UNET DtMin= 0
UNET MaxCRTS= 0
UNET WFStab= 0
UNET SFStab= 0
UNET WFX= 1
UNET SFX= 1
UNET Gravity=32.174
UNET 1D Methodology=Finite Difference
UNET DSS MLevel= 1
UNET Pardiso=0
UNET DZMax Abort= 0
UNET Use Existing IB Tables= 0
UNET Froude Reduction=False
UNET Froude Limit= 0
UNET Froude Power= 0
UNET D1 Cores= 0
UNET WindReference=Eulerian
UNET WindDragFormulation=Hsu (1988)
UNET D2 Coriolis=0
UNET D2 Cores= 0
UNET D2 Theta= 1
UNET D2 Theta Warmup= 1
UNET D2 Z Tol= 0.01
UNET D2 Volume Tol= 0.01
UNET D2 Max Iterations= 20
UNET D2 Equation= 0
UNET D2 RampUpFraction=0.1
UNET D2 TimeSlices= 1
UNET D2 Turbulence Formulation=Non-Conservative (original)
UNET D2 Eddy Viscosity=0.3
UNET D2 Transverse Eddy Viscosity=0.1
UNET D2 Smagorinsky Mixing=0
UNET D2 BCVolumeCheck=0
UNET D2 Cores=0
UNET D2 SolverType=PARDISO (Direct)
UNET D2 Minimum Iterations= 2147483647
UNET D2 Maximum Iterations= 2147483647
UNET D2 Restart Number= 10
UNET D2 Relaxation Coeff=1.3
UNET D2 SOR Precondition Iterations= 10
UNET D2 ILUT Maximum Fill= 8
UNET D2 ILUT Tolerance=1E-08
UNET D1D2 MaxIter= 0
UNET D1D2 ZTol=0.01
UNET D1D2 QTol=0.1
UNET D1D2 MinQTol=1
Write IC File= 0
Write IC File at Fixed DateTime=0
Write IC File at Sim End=0
Echo Input=False
Echo Parameters=False
Echo Output=False
Write Detailed= 0
HDF Write Warmup=0
HDF Write Time Slices=0
HDF Flush=0
HDF Compression= 1
HDF Chunk Size= 1
HDF Spatial Parts= 1
HDF Use Max Rows=0
HDF Fixed Rows= 1
Calibration Method= 0
Calibration Iterations= 20
Calibration Max Change=0.05
Calibration Tolerance=0.2
Calibration Maximum=1.5
Calibration Minimum=0.5
Calibration Optimization Method= 1
WQ AD Non Conservative
WQ ULTIMATE=-1
WQ Max Comp Step=1HOUR
WQ Output Interval=15MIN
WQ Output Selected Increments= 0
WQ Output face flow=0
WQ Output face velocity=0
WQ Output face area=0
WQ Output face dispersion=0
WQ Output cell volume=0
WQ Output cell surface area=0
WQ Output cell continuity=0
WQ Output cumulative cell continuity=0
WQ Output face conc=0
WQ Output face dconc_dx=0
WQ Output face courant=0
WQ Output face peclet=0
WQ Output face adv mass=0
WQ Output face disp mass=0
WQ Output cell mass=0
WQ Output cell source sink temp=0
WQ Output nsm pathways=0
WQ Output nsm derived pathways=0
WQ Create Restart=0
WQ Fixed Restart=0
WQ System Summary=0
WQ Write To DSS=0
Sorting and Armoring Iterations= 10
XS Update Threshold= 0.02
Bed Roughness Predictor= 0
Hydraulics Update Threshold= 0.02
Energy Slope Method= 1
Volume Change Method= 1
Sediment Retention Method= 0
Sediment TS Multiplier= 1
Warm Up Method= 0
XS Weighting Method= 0
Number of US Weighted Cross Sections= 1
Number of DS Weighted Cross Sections= 1
Upstream XS Weight=0
Main XS Weight=1
Downstream XS Weight=0
Number of DS XS's Weighted with US Boundary= 1
Upstream Boundary Weight= 1
Weight of XSs Associated with US Boundary= 0
Number of US XS's Weighted with DS Boundary= 1
Downstream Boundary Weight= 0.5
Weight of XSs Associated with DS Boundary= 0.5
Percentile Method= 0
Sediment Output Level= 3
Mass or Volume Output= 0
Output Increment Type= 1
Profile and TS Output Increment= 1
Transport Output Increment 1
XS Output Flag= 0
XS Output Increment= 10
Read HDF5 Sediment Hotstart= 0
Sediment Hotstart Type= 0
Write Gradation File= 0
Read Gradation Hotstart= 0
Write HDF5 File= 1
Write Binary Output= 1
Write DSS Sediment File= 0
DSS Sediment Output Type= 1
SV Curve= 0
Specific Gage Flag= 0
Subcell Erosion Methods= 0
Subcell Deposition Methods= 0
Advection Scheme= 1
Matrix Solver= 0
Implicit Weighting Factor= 1
Maximum Outer Loop Convergence Iterations= 5
Convergence Maximum Absolute= 0.001
Convergence RMSE= 0.0001
Grain Fractions Max Abs Error= 0.001
Max Subgrid Regions= 1
Max Subgrid Length Scale= 3.402823E+38
Initial Layer Thickness= 3.402823E+38
Min Layer Thickness= 3.402823E+38
Max Layer Thickness= 3.402823E+38
Number of Layers= 5

--- KENSCK.f01 (steady flow) ---

Flow Title=Flow
Program Version=6.00
Number of Profiles= 6
Profile Names=01pct,10pct,04pct,02pct,0_2pct,01plus
River Rch & RM=KENSCK,Main,6928
     577     305     406     489     807     854
River Rch & RM=KENSCK,Main,5008
     651     346     458     552     907     962
River Rch & RM=KENSCK,Main,3446
     737     393     521     625    1020    1090
Boundary for River Rch & Prof#=KENSCK,Main            , 1
Up Type= 0
Dn Type= 3
Dn Slope=0.06704
Boundary for River Rch & Prof#=KENSCK,Main            , 2
Up Type= 0
Dn Type= 3
Dn Slope=0.06704
Boundary for River Rch & Prof#=KENSCK,Main            , 3
Up Type= 0
Dn Type= 3
Dn Slope=0.06704
Boundary for River Rch & Prof#=KENSCK,Main            , 4
Up Type= 0
Dn Type= 3
Dn Slope=0.06704
Boundary for River Rch & Prof#=KENSCK,Main            , 5
Up Type= 0
Dn Type= 3
Dn Slope=0.06704
Boundary for River Rch & Prof#=KENSCK,Main            , 6
Up Type= 0
Dn Type= 3
Dn Slope=0.06704
DSS Import GetInterval= 0
DSS Import GetPeak= 0
DSS Import FillOption= 0

--- KENSCK.g01 (geometry) ---

Geom Title=Geometry
Program Version=6.10

River Reach=KENSCK          ,Main
Reach XY= 30
2182484.07099999      485936.5222182453.94000001486117.758000016
     2182546.443486218.3139999962182665.73999999486528.192000017
2182565.95900001486928.4190000152182590.42250006487374.076000005
2182631.38633893487496.7260810582182535.69400002487676.516000018
2182516.72400002487952.0150000162182441.78528516488008.989307791
2182394.57799999488186.6020000132182537.74000002488469.578000009
2182499.85900001488763.0370000152182733.15000002488994.927000016
2182701.79900004489079.3110000042182703.58300002 489337.13500002
2182803.53700002489572.1880000082182650.65500002489891.017000005
2182569.31438817 490168.595804142182757.99750008490342.264499992
2182698.55250002490495.488500014     2182685.355490719.307000011
      2182777.55491026.9920000142182674.47600003 491167.56400001
2182663.82224052491324.0735287522182740.79184683 491552.63841027
2182733.27749999491646.0330000072182663.65700002491841.999000013
2182499.11900003492016.4839999972182412.51139815492425.112980902

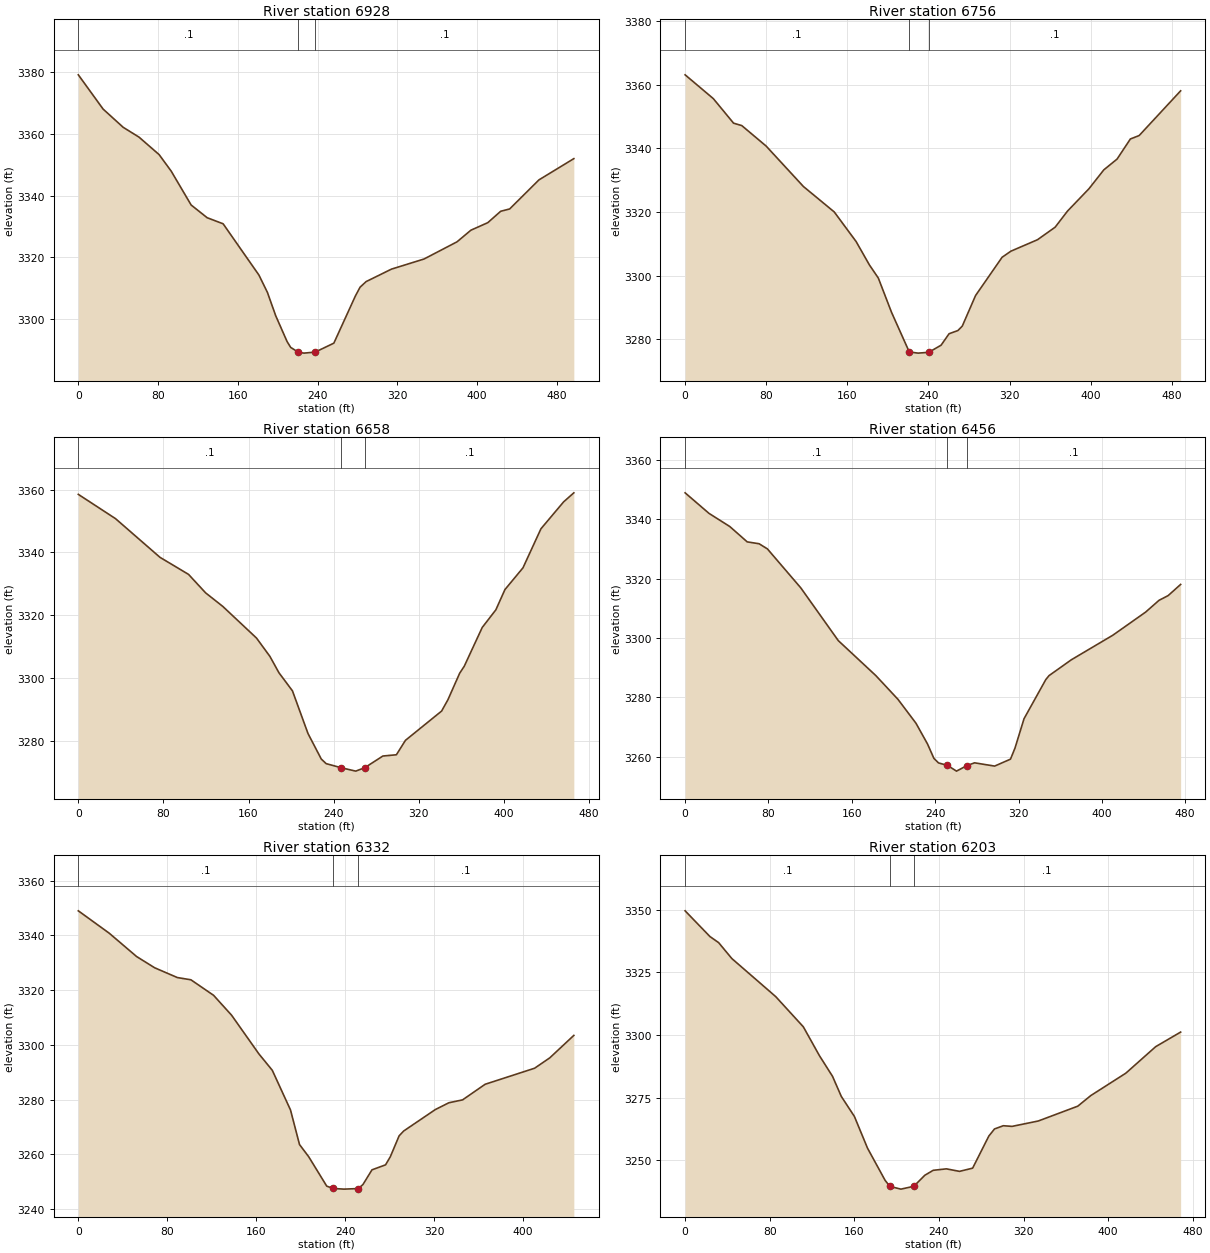
Type RM Length L Ch R = 1 ,6928    ,164.9,171.8,177.3
XS GIS Cut Line= 4
2182295.34152173486225.3423466242182447.54293706486212.713091871
2182587.12388626486085.6032021692182733.01506852486031.113724456
#Sta/Elev= 30
       0 3378.97    24.9  3367.9      45 3362.03      61 3358.83    81.1  3353.2
    93.2 3347.87   113.2 3336.94   129.3 3332.83   145.3 3330.87   181.2 3314.33
   189.7 3308.75   198.1 3301.16   209.5 3292.83   213.1 3290.95   220.8  3289.4
   226.5 3289.11   237.8 3289.46   256.4 3292.33     278 3307.55   282.7 3310.39
   288.8 3312.21   314.2 3316.23   346.9  3319.5     380 3325.05   393.9  3328.8
   410.9 3331.24   423.8 3334.91   432.8 3335.66   462.2 3345.05   497.2 3351.91
#Mann= 3 ,-1,0
       0      .1       0   220.8    .045       0   237.8      .1       0
Bank Sta=220.8,237.8
XS Rating Curve= 0 ,0
Exp/Cntr(USF)=0,0
Exp/Cntr=0.3,0.1

Type RM Length L Ch R = 1 ,6756    ,97.8,98.8,100
XS GIS Cut Line= 3
2182348.40574539486333.7949368442182508.18033123486342.838781326
2182809.64181394486211.703036348
#Sta/Elev= 30
       0 3363.06    27.8  3355.6    47.8 3347.89    55.9 3347.13    79.9 3340.71
   116.7 3328.01   147.1 3320.03   168.7 3310.73   181.8  3303.4   190.6 3299.28
   203.6 3288.54   221.1  3276.1   229.8 3275.72   240.3 3275.97   252.5 3278.21
   260.4 3281.81   269.1 3282.81   273.4  3284.2   286.5 3293.79   312.7 3305.81
   321.4 3307.72   347.6 3311.31     365 3315.24   377.1 3320.26   398.4 3327.32
     413 3333.23   426.1 3336.62   439.2 3342.92   447.9 3344.01   488.8 3358.04
#Mann= 3 ,-1,0
       0      .1       0   221.1    .045       0   240.3      .1       0
Bank Sta=221.1,240.3
XS Rating Curve= 0 ,0
Exp/Cntr(USF)=0,0
Exp/Cntr=0.3,0.1

Type RM Length L Ch R = 1 ,6658    ,192.6,201.9,213.6
XS GIS Cut Line= 3
2182360.69671422486442.5072267752182534.23672074486433.098431241
2182809.18263468486334.828788996
#Sta/Elev= 30
       0 3358.46      35 3350.72    76.8  3338.4   103.6 3332.98   119.7 3327.08
   135.7 3322.81   167.5  3312.7   180.1 3306.86   188.6 3301.65   201.3 3295.88
   215.9  3282.3   228.4 3274.16     233  3272.7   247.2 3271.39   260.8 3270.32
   269.3 3271.42   286.3 3275.13     299 3275.53   307.5 3280.12   341.5 3289.45
   347.4 3293.03   358.5 3301.51   362.8 3303.73   379.7 3316.08   392.5 3321.69
     401 3328.12     418 3335.07   434.9 3347.51   456.2 3356.07   465.8 3358.95
#Mann= 3 ,-1,0
       0      .1       0   247.2    .045       0   269.3      .1       0
Bank Sta=247.2,269.3
XS Rating Curve= 0 ,0
Exp/Cntr(USF)=0,0
Exp/Cntr=0.3,0.1

Type RM Length L Ch R = 1 ,6456    ,126.3,123.9,120.5
XS GIS Cut Line= 3
2182397.27041944486558.0357630982182585.05300932486565.920278529
2182851.27011038486674.786764753
#Sta/Elev= 30
       0 3348.97    22.9 3342.05    42.9  3337.6    59.6 3332.43      71  3331.8
      79 3330.06     111 3316.93     147 3299.14   183.1 3287.32   204.3 3279.33
   221.6 3271.26   232.7 3264.25   238.8 3259.41   243.2 3257.89   251.8 3257.05
   260.5 3255.12   270.5 3256.99   277.8 3257.92   297.1 3256.82   312.3 3259.16
   316.6 3262.88   325.3  3272.8   346.2    3286   349.3 3287.33   370.7 3292.67
   410.6 3300.97     442 3308.75   454.9 3312.73   463.6 3314.31   475.6 3318.08
#Mann= 3 ,-1,0
       0      .1       0   251.8    .045       0   270.5      .1       0
Bank Sta=251.8,270.5
XS Rating Curve= 0 ,0
Exp/Cntr=0.3,0.1

Type RM Length L Ch R = 1 ,6332    ,128.5,129,130.8
XS GIS Cut Line= 2
2182388.69406177486668.1782842592182826.47163173486752.121070733
#Sta/Elev= 30
       0 3348.97    27.8  3340.8    52.4 3332.28    68.7 3328.16    89.1 3324.59
   101.3 3323.77   121.7  3318.1   137.9 3310.83   162.4 3296.73   174.5 3290.71
   190.9 3276.21     199 3263.58   207.2 3259.17   223.5 3248.38   229.4 3247.53
     239 3247.29     252  3247.5   256.1 3248.99   264.2 3254.34   276.4 3256.16
   280.7 3259.12   288.6 3266.75   292.7 3268.52   321.2 3276.36   333.4 3278.85
   345.7  3279.9     366  3285.6   410.5 3291.46   424.2 3295.27   445.8 3303.46
#Mann= 3 ,-1,0
       0      .1       0   229.4    .045       0     252      .1       0
Bank Sta=229.4,252
XS Rating Curve= 0 ,0
Exp/Cntr(USF)=0,0
Exp/Cntr=0.3,0.1

Type RM Length L Ch R = 1 ,6203    ,184.4,180,176.3
XS GIS Cut Line= 2
2182385.50636101486782.9355113372182838.15986782486904.068139918
#Sta/Elev= 30
       0 3349.56    23.5 3339.29    31.7 3336.87    44.2 3330.51    85.7 3315.32
   111.8 3303.27     127 3291.77   139.4 3283.52   147.7  3275.5   160.1  3267.5
   172.5 3254.84   189.1 3242.03   193.63239.588   204.1  3238.5   216.3 3239.63
   226.7 3244.04   234.6 3246.01   247.1 3246.59   259.5 3245.59   271.9 3246.87
   287.2 3259.66   292.6 3262.52   300.9  3263.8   309.2 3263.54     334 3265.69
   371.3  3271.6   383.7 3275.85   416.8 3284.78     445 3295.35   468.6 3301.17
#Mann= 3 ,0,0
       0      .1       0   193.6    .045       0   216.3      .1       0
Bank Sta=193.6,216.3
XS Rating Curve= 0 ,0
Exp/Cntr(USF)=0,0
Exp/Cntr=0.3,0.1

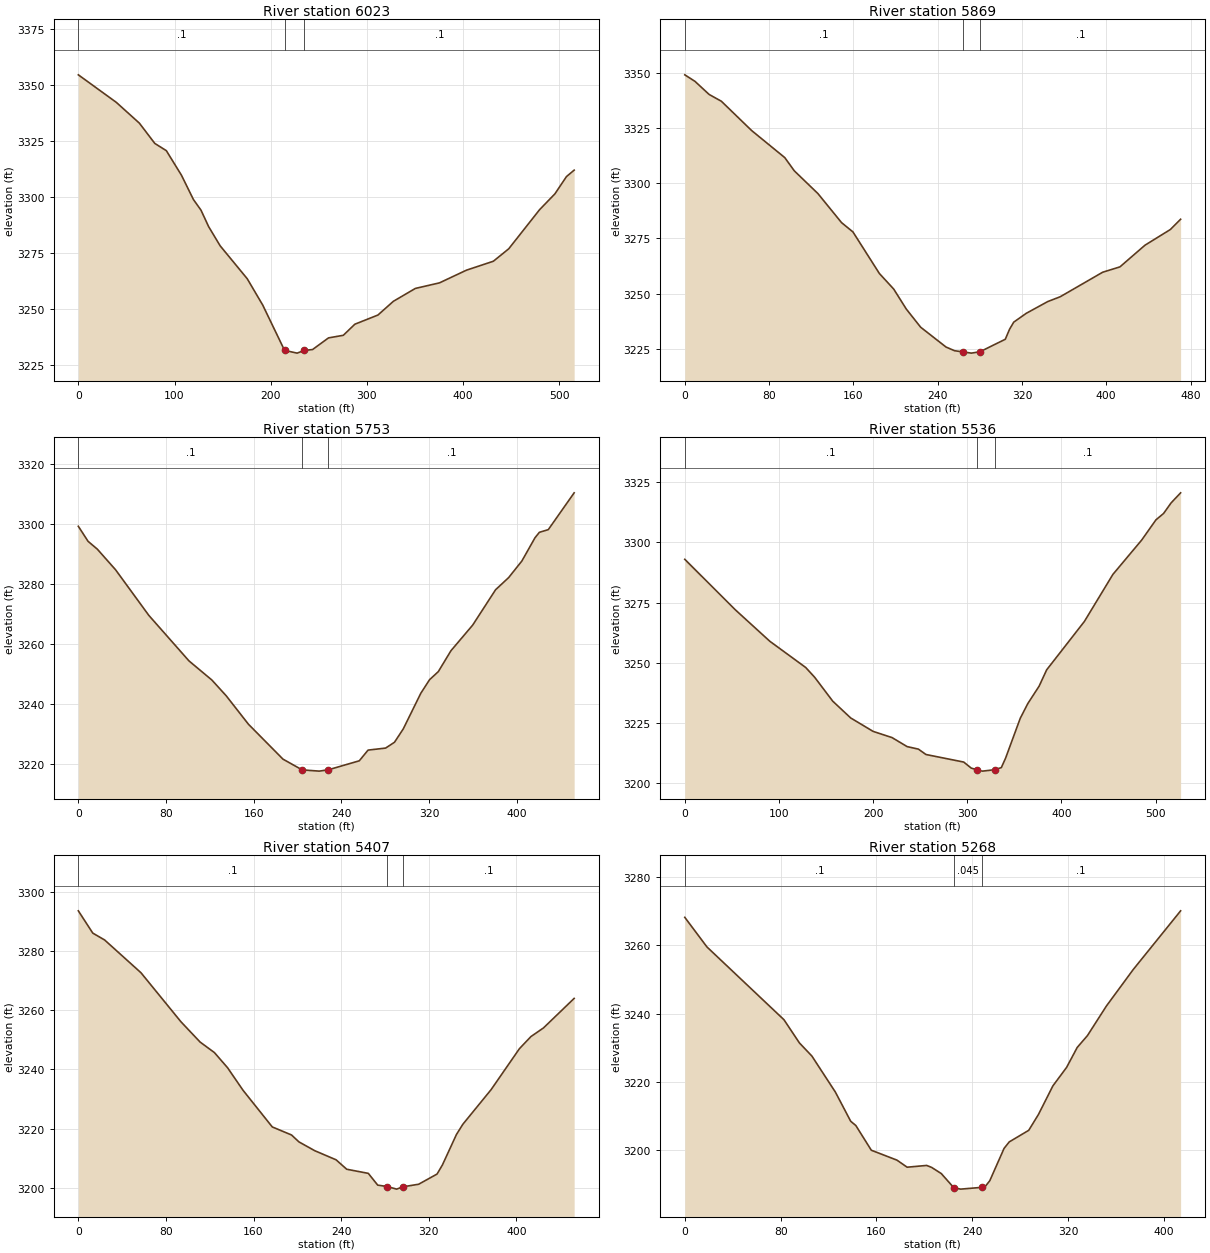
Type RM Length L Ch R = 1 ,6023    ,155.6,153.5,152.4
XS GIS Cut Line= 2
2182340.67246067487012.2444175222182856.17159609487015.259032349
#Sta/Elev= 30
       0 3354.54    39.5 3342.26    63.5 3332.98    79.5 3323.96    91.5 3320.73
   107.2  3309.8   119.7 3298.92   127.5 3294.23   135.5 3286.85   147.4 3278.34
   175.6 3263.64   191.7 3251.91  214.42 3231.69   227.5 3230.47   235.1 3231.69
   243.5 3232.06   260.1 3237.26   275.5 3238.42   287.5 3243.36   311.5 3247.45
   327.5 3253.56   350.4 3259.31   375.5  3261.8   403.5 3267.45   431.5 3271.43
   447.5 3276.99   479.5 3294.39   495.5 3301.48   507.5 3309.17   515.5 3312.05
#Mann= 3 ,0,0
       0      .1       0  214.42    .045       0   235.1      .1       0
Bank Sta=214.42,235.1
XS Rating Curve= 0 ,0
Exp/Cntr(USF)=0,0
Exp/Cntr=0.3,0.1

Type RM Length L Ch R = 1 ,5869    ,115.9,116.4,117
XS GIS Cut Line= 3
 2182335.5657159487075.1414136172182525.76519411487171.835003098
 2182781.8438212487147.395963998
#Sta/Elev= 30
       0 3349.06     9.7 3346.09    23.1 3340.17    34.7  3337.1    63.5  3323.8
    94.9 3311.57   103.9  3305.6   126.3 3295.31   148.8 3282.12   159.6 3277.91
   184.7 3259.08   198.3 3252.03   210.2 3243.01   223.8 3234.79   247.9  3225.8
     256 3224.12     264 3223.59     272 3223.03   280.1 3223.64   304.2 3229.31
   308.2 3233.81   312.2 3237.06   324.1 3241.06   344.4 3246.36   356.4 3248.58
   396.6 3259.66     413 3262.09   436.8 3271.91   460.9 3279.02   470.6 3283.66
#Mann= 3 ,-1,0
       0      .1       0     264    .045       0   280.1      .1       0
Bank Sta=264,280.1
XS Rating Curve= 0 ,0
Exp/Cntr(USF)=0,0
Exp/Cntr=0.3,0.1

Type RM Length L Ch R = 1 ,5753    ,216.7,217,216.5
XS GIS Cut Line= 3
2182387.63149485487233.463884306 2182555.5170678487284.467096341
2182831.78446631487266.403458745
#Sta/Elev= 30
       0 3299.35     8.9 3294.32    17.3 3291.72      34 3284.81    64.3 3269.59
   100.9 3254.39   121.8 3247.99   134.9 3242.72   155.2 3233.21   186.7 3221.55
   204.2 3217.96   219.8 3217.55   228.2 3218.01   256.3    3221   264.3 3224.57
   280.3 3225.25   288.4 3227.19   296.4 3231.65   312.4 3243.55   320.4  3248.1
   328.4  3250.8   339.9 3257.77   359.8 3266.37   380.6 3278.14   392.6 3282.23
   404.6 3287.75   416.6 3295.53   420.6 3297.34   428.7 3298.23   452.3 3310.53
#Mann= 3 ,-1,0
       0      .1       0   204.2    .045       0   228.2      .1       0
Bank Sta=204.2,228.2
XS Rating Curve= 0 ,0
Exp/Cntr(USF)=0,0
Exp/Cntr=0.3,0.1

Type RM Length L Ch R = 1 ,5536    ,119.6,129.3,138.4
XS GIS Cut Line= 3
2182344.50433784487387.9834682892182512.27473628487497.099032823
2182838.26620689487479.691188543
#Sta/Elev= 30
       0 3292.97    53.5 3272.06    90.3 3258.94   128.4 3248.05     138 3243.95
   157.1 3234.07   176.2 3227.08     200 3221.51   220.1 3218.93   236.1 3215.19
   248.1 3214.14   256.1 3211.91   296.2 3208.77   304.2 3206.26   310.1 3205.57
   316.2    3205   329.3 3205.59   336.2 3206.48   340.7 3210.39   356.3 3226.96
   364.3 3233.06   376.3 3240.28   384.3 3247.05   424.4 3267.17   454.7 3286.72
   485.2 3300.95   500.4 3309.37   508.5 3312.02   516.5 3316.41   526.6 3320.59
#Mann= 3 ,0,0
       0      .1       0   310.1    .045       0   329.3      .1       0
Bank Sta=310.1,329.3
XS Rating Curve= 0 ,0
Exp/Cntr=0.3,0.1

Type RM Length L Ch R = 1 ,5407    ,145,138.2,133
XS GIS Cut Line= 3
2182318.17297834487467.9083930682182476.14781694487536.441595107
2182707.30217636487695.578013401
#Sta/Elev= 30
       0 3293.52    13.2    3286      24 3283.69    57.2 3272.63    93.7 3256.09
   111.2 3249.24   124.3 3245.68   136.3 3240.57   150.4 3232.97   177.1  3220.6
   194.7 3217.88   201.5 3215.54   215.9 3212.58   235.4  3209.5   245.1 3206.32
   264.8 3204.93   273.4 3200.96     282 3200.49   290.7 3199.61   296.4 3200.39
   310.8 3201.26   327.6  3204.7   332.5 3207.78   345.3 3218.04   351.1 3221.47
     377  3233.2   402.8 3246.99   413.3 3251.08   424.8 3254.01   452.8 3263.97
#Mann= 3 ,0,0
       0      .1       0     282    .045       0   296.4      .1       0
Bank Sta=282,296.4
XS Rating Curve= 0 ,0
Exp/Cntr(USF)=0,0
Exp/Cntr=0.3,0.1

Type RM Length L Ch R = 1 ,5268    ,150.2,148.8,146.7
XS GIS Cut Line= 3
2182306.87640913487657.4280843422182481.13738358487724.369800137
2182705.33900315487761.559642245
#Sta/Elev= 30
       0 3268.23    18.5 3259.56    82.8 3238.24    95.7 3231.45   106.1 3227.61
   125.7 3217.06   138.5 3208.51   142.8 3207.26   155.7 3200.03   177.1 3197.13
   185.6 3195.06   201.9 3195.58     206 3195.01   214.1  3193.2   224.63189.046
   230.3 3188.64   247.83189.153   250.6 3189.33   254.6  3191.1   266.5 3200.55
   270.8 3202.46   287.1 3205.86   295.2 3210.49   307.3 3218.89   318.7 3224.28
   327.6 3230.14   336.1 3233.59   351.9 3242.24   374.3 3252.93   413.9 3270.14
#Mann= 3 ,-1,0
       0      .1       0   224.6    .045       0   247.8      .1       0
Bank Sta=224.6,247.8
XS Rating Curve= 0 ,0
Exp/Cntr(USF)=0,0
Exp/Cntr=0.3,0.1

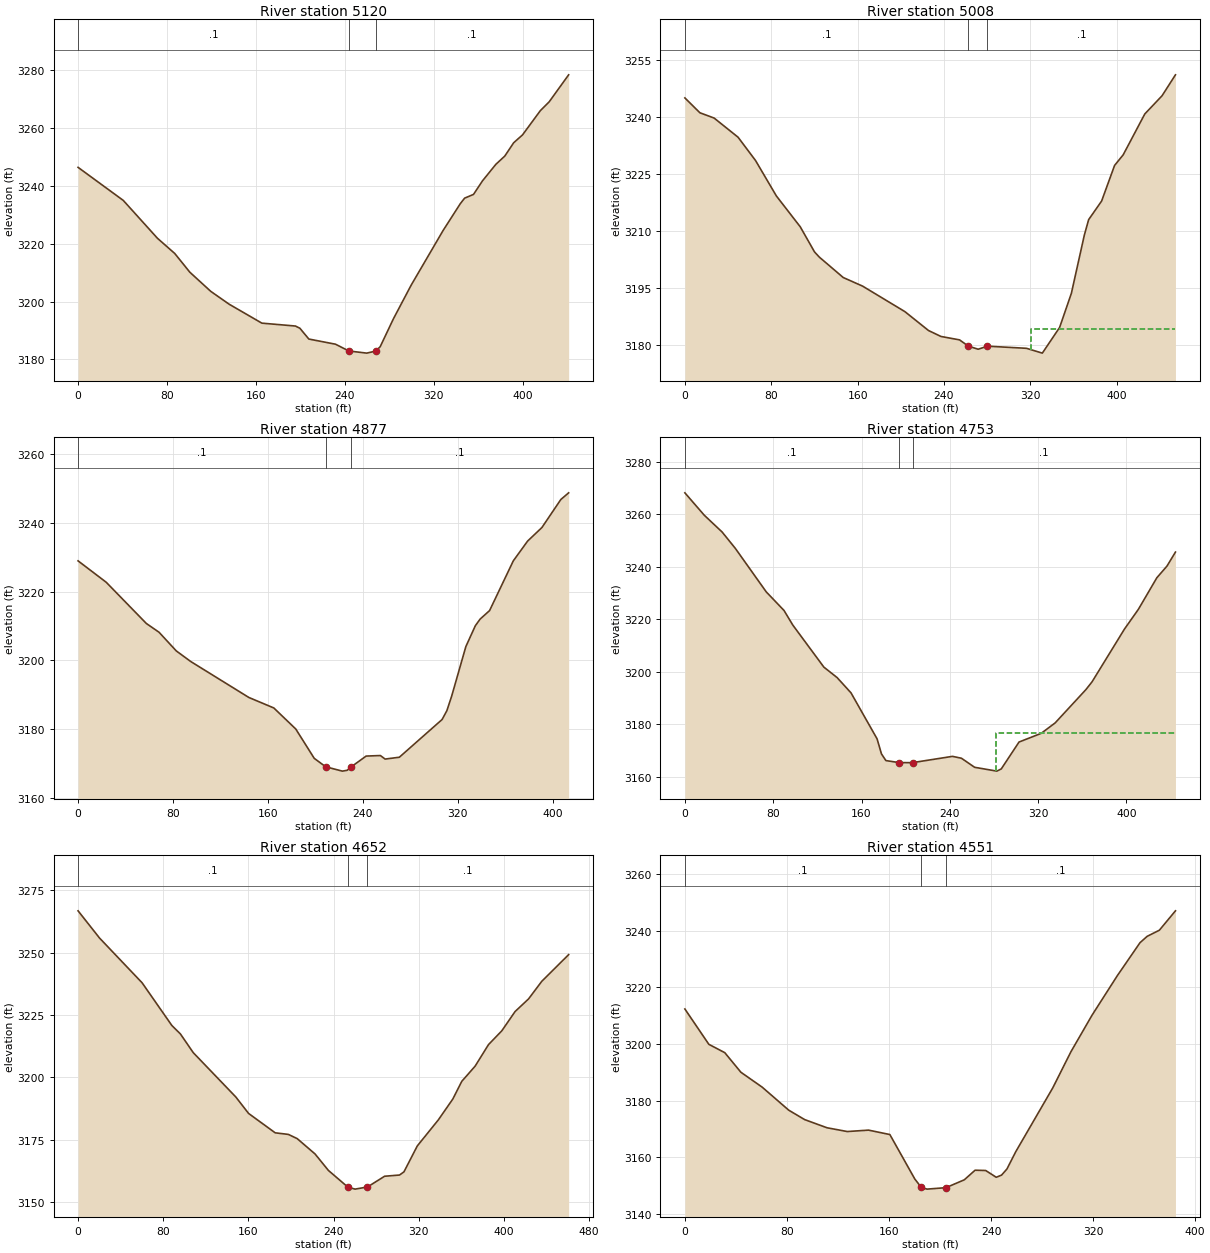
Type RM Length L Ch R = 1 ,5120    ,97.2,112,124
XS GIS Cut Line= 3
2182288.97126755487798.6113706772182418.87701812487874.137144647
2182709.56589522487891.200918617
#Sta/Elev= 30
       0 3246.44    40.7 3234.99    71.5 3221.87      87 3216.63   100.6 3210.14
   119.4 3203.52   135.9 3199.08   165.4 3192.51   195.6 3191.51   199.6 3190.75
   207.7    3187   231.7 3185.22   243.7 3182.87   259.8 3182.13   267.9 3182.85
   271.9 3184.35   283.8 3194.01   299.8 3205.68   328.5 3224.57   343.9 3233.81
   347.9 3235.78   355.9 3237.08   363.9 3241.73     376 3247.49     384 3250.33
     392 3254.94     400 3257.68     416 3266.05     424 3269.13   441.5 3278.47
#Mann= 3 ,-1,0
       0      .1       0   243.7    .045       0   267.9      .1       0
Bank Sta=243.7,267.9
XS Rating Curve= 0 ,0
Exp/Cntr=0.3,0.1

Type RM Length L Ch R = 1 ,5008    ,146.8,130.7,120
XS GIS Cut Line= 4
 2182267.6541806487822.4639051152182434.92165677487901.915956293
2182532.14587729488039.9116241272182632.50636298488042.002467579
#Sta/Elev= 30
       0 3244.99    13.9 3241.08    27.1 3239.68    49.3 3234.63    65.5 3228.48
    84.7 3219.19   106.9 3211.03   120.1 3204.42   124.6 3203.04   146.7 3197.68
   164.6 3195.42   203.8  3188.7   225.7 3183.72   237.2 3182.16   254.4 3181.26
   262.6 3179.61   271.7  3178.8   280.3  3179.6   316.4 3179.04   331.1 3177.77
   347.1 3184.53     358 3193.52     370 3208.85     374 3212.93     386 3217.82
     398  3227.2     406    3230     426 3240.76     442 3245.56   454.4 3251.07
#Mann= 3 ,-1,0
       0      .1       0   262.6    .045       0   280.3      .1       0
#XS Ineff= 2 , 0
                          320.56         3184.05
Permanent Ineff=
       F       F
Bank Sta=262.6,280.3
XS Rating Curve= 0 ,0
Exp/Cntr(USF)=0,0
Exp/Cntr=0.3,0.1

Type RM Length L Ch R = 1 ,4877    ,125.3,124,127.4
XS GIS Cut Line= 3
2182238.87212642487988.948962565 2182390.8191956488080.329717459
2182626.70905126488085.642552046
#Sta/Elev= 30
       0 3228.93    23.7 3222.72    57.5 3210.75    68.2  3208.2    82.7 3202.79
    94.9  3199.7   143.9 3189.25   164.9 3186.21   183.4  3180.1     199 3171.56
   208.73169.111   222.7 3167.86   226.7  3168.1   230.3 3169.15   242.7 3172.23
   254.7 3172.39   258.7 3171.36   270.7  3171.9   306.7 3182.86   310.7 3185.41
   314.7 3189.58   326.7 3204.03   334.7 3210.09   338.7 3212.01   346.7 3214.49
   366.7 3228.94   378.7 3234.66   390.8 3238.62   406.7 3246.74   413.3 3248.69
#Mann= 3 ,-1,0
       0      .1       0   208.7    .045       0   230.3      .1       0
Bank Sta=208.7,230.3
XS Rating Curve= 0 ,0
Exp/Cntr(USF)=0,0
Exp/Cntr=0.3,0.1

Type RM Length L Ch R = 1 ,4753    ,106.6,100.5,106.2
XS GIS Cut Line= 4
2182190.58569096488195.3553805682182314.00858607488203.312113136
2182512.15782002 488183.835906382182628.20967969488147.579607689
#Sta/Elev= 30
       0 3268.21    17.6 3259.66    33.7 3253.29    45.7 3247.04    73.7 3230.46
    89.8 3223.37    97.8 3217.79   125.9 3201.78   137.9 3197.79   150.5 3191.96
   174.1 3174.44   178.1 3168.69   182.1 3166.15   194.2 3165.37   206.2 3165.36
   242.4 3167.76   250.5 3167.05   262.5 3163.59   282.6 3162.13   286.6 3162.96
   302.7 3173.22   322.8 3176.53   335.4  3180.5   363.2 3193.16   368.9  3196.2
   398.2 3216.27   410.8 3223.79   427.6 3235.87   436.7 3240.27   444.4 3245.62
#Mann= 3 ,0,0
       0      .1       0   194.2    .045       0   206.2      .1       0
#XS Ineff= 2 , 0
                          281.52         3176.71
Permanent Ineff=
       F       F
Bank Sta=194.2,206.2
XS Rating Curve= 0 ,0
Exp/Cntr(USF)=0,0
Exp/Cntr=0.3,0.1

Type RM Length L Ch R = 1 ,4652    ,101.5,101,101.4
XS GIS Cut Line= 3
2182203.96050808488299.3908015122182369.53270636488299.029260561
2182652.32697298 488213.87299855
#Sta/Elev= 30
       0 3266.71    20.2  3255.8    60.2 3237.87    88.2 3220.75    96.2 3217.39
   108.2 3209.93   148.2 3192.17   160.2 3185.58   185.2 3177.82   197.6 3177.18
   205.9 3175.49   222.6 3169.37   235.2 3162.76  253.47 3156.08   260.2 3155.27
   271.9 3156.13     288 3160.43     302 3160.91   306.2  3162.2   318.7 3172.56
   338.5 3183.01   352.1 3191.36   360.5 3198.43     373 3204.49   385.6 3213.13
   398.1 3218.66   410.6 3226.39   423.2 3231.42   435.7  3238.5   460.9 3249.17
#Mann= 3 ,0,0
       0      .1       0  253.47    .045       0   271.9      .1       0
Bank Sta=253.47,271.9
XS Rating Curve= 0 ,0
Exp/Cntr=0.3,0.1

Type RM Length L Ch R = 1 ,4551    ,163.6,173,182.6
XS GIS Cut Line= 2
2182294.12560612488425.6639656082182662.83632645488316.219573118
#Sta/Elev= 30
       0 3212.35    18.8 3199.86    31.3 3196.91    43.9    3190    60.6 3184.73
    81.4  3176.6    93.9 3173.26   111.4 3170.38   127.3 3169.04     144 3169.54
   160.7 3167.98   180.3 3152.24   185.4 3149.28   189.9 3148.69   204.7 3149.21
   219.1 3151.99   227.5 3155.37   235.8 3155.28   244.1 3152.88   248.3 3153.65
   252.5 3155.81   259.4 3161.91   288.4 3184.45   302.6 3197.19   319.2 3210.15
   339.1 3224.17   356.8 3235.77   362.4 3238.02     372 3240.19   384.6 3247.04
#Mann= 3 ,-1,0
       0      .1       0   185.4    .045       0   204.7      .1       0
Bank Sta=185.4,204.7
XS Rating Curve= 0 ,0
Exp/Cntr(USF)=0,0
Exp/Cntr=0.3,0.1

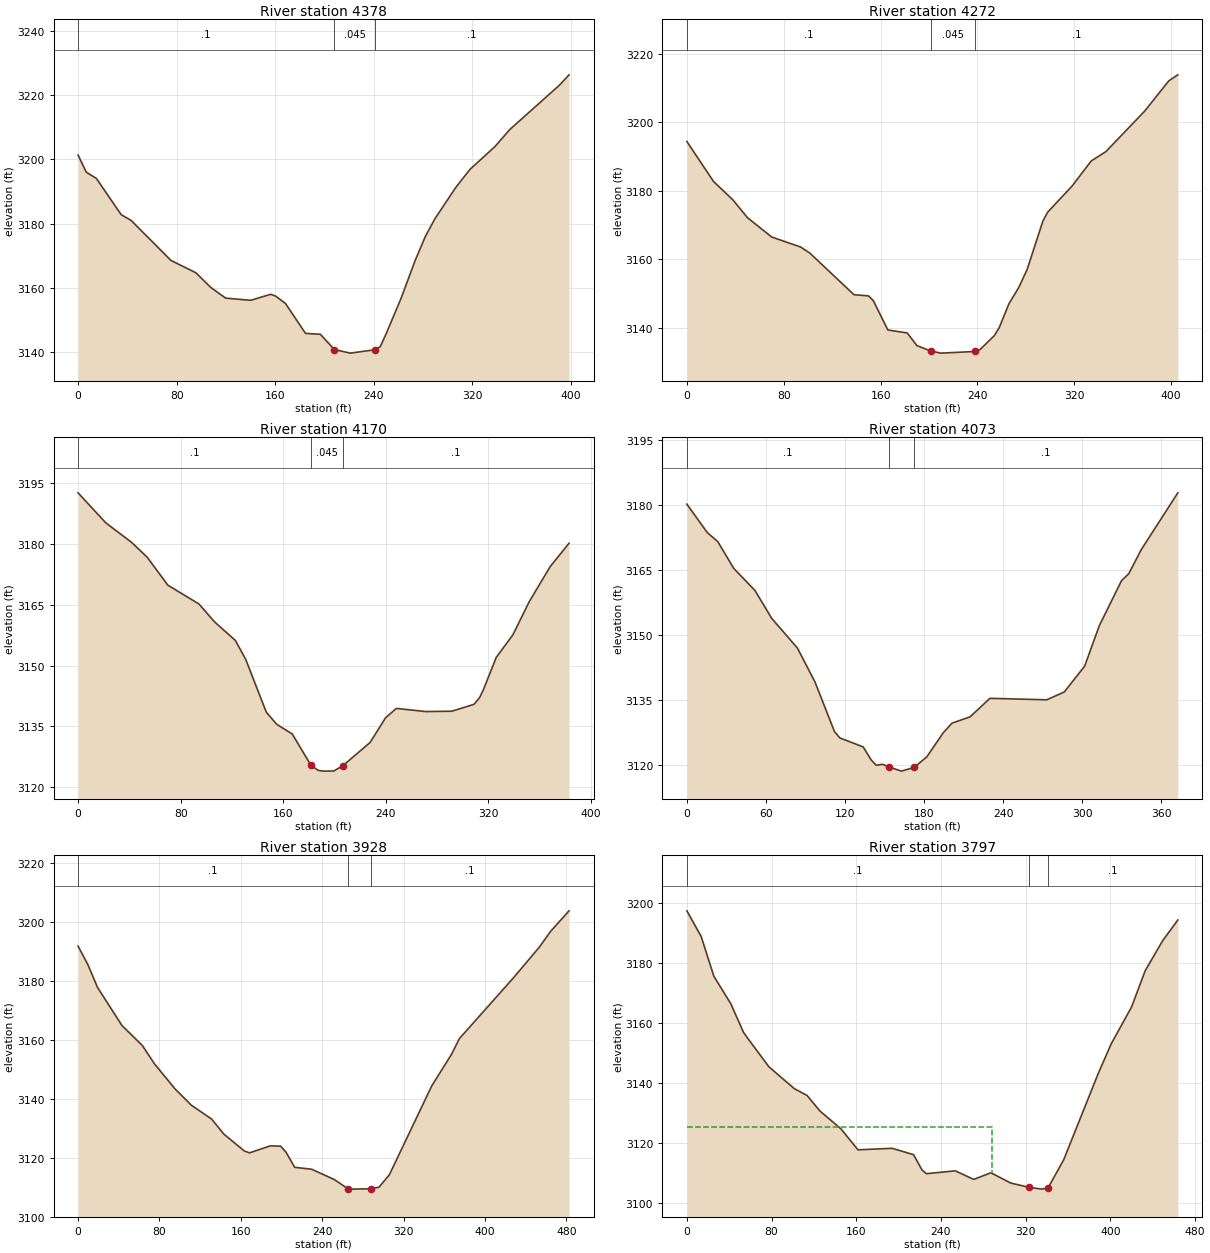
Type RM Length L Ch R = 1 ,4378    ,108.4,105.9,101.7
XS GIS Cut Line= 2
2182301.56357454488491.5431144862182695.77590089488549.984294942
#Sta/Elev= 30
       0 3201.34     6.7 3195.99    14.8 3194.09      35 3182.76    43.1 3180.95
    75.4 3168.49    95.6 3164.65   107.8 3160.04   119.8 3156.74   140.1 3156.06
   156.3 3157.93   160.3 3157.39   168.4 3155.05   184.6 3145.75   196.7 3145.46
     208 3140.71     221 3139.59   241.2 3140.66   245.3 3141.63   250.3 3145.85
   262.3 3156.81   273.6 3168.48   281.9 3175.99   289.7 3181.54   306.6 3191.26
     318 3196.85   338.3 3203.97   350.4 3209.31   390.5 3223.07   398.5 3226.37
#Mann= 3 ,0,0
       0      .1       0     208    .045       0   241.2      .1       0
Bank Sta=208,241.2
XS Rating Curve= 0 ,0
Exp/Cntr(USF)=0,0
Exp/Cntr=0.3,0.1

Type RM Length L Ch R = 1 ,4272    ,97.4,102.2,106.1
XS GIS Cut Line= 2
2182302.17647721488631.4525756922182707.64217145488623.916038624
#Sta/Elev= 30
       0 3194.35      22  3182.7      38 3177.33      50 3172.15      70  3166.5
      94 3163.56   101.6 3161.78     138 3149.66     150 3149.31     154 3147.92
     166 3139.36     182  3138.5     190 3134.81     202 3133.15     210 3132.61
     238 3133.09     242  3133.6     254 3137.74     258 3140.07     266 3147.01
     274 3151.68     281 3156.98     294 3171.09     298 3173.74   318.1 3181.34
     334 3188.69   346.1 3191.41   378.1 3203.22   398.1 3212.08   405.5 3213.81
#Mann= 3 ,-1,0
       0      .1       0     202    .045       0     238      .1       0
Bank Sta=202,238
XS Rating Curve= 0 ,0
Exp/Cntr(USF)=0,0
Exp/Cntr=0.3,0.1

Type RM Length L Ch R = 1 ,4170    ,109.5,97.2,85.9
XS GIS Cut Line= 3
2182306.87640913 488696.618529542182548.07909937488731.683237814
2182676.64969638488678.554891945
#Sta/Elev= 30
       0 3192.68    21.5  3185.3    41.7 3180.45    53.9 3176.78      70 3169.88
    94.3 3165.22   106.4 3160.82   122.6 3156.25   130.7 3151.59   146.8 3138.51
   154.9 3135.52     167 3133.13   181.6 3125.41   187.2 3124.15   191.3 3123.95
   199.4 3123.98   206.3 3125.24   227.7 3131.01   239.8 3137.11   248.2 3139.44
   271.2 3138.66   291.5 3138.75   308.8 3140.45   313.1 3142.09   316.2 3144.12
   326.1 3152.02   339.1 3157.61     352 3165.87   368.2 3174.46   382.9 3180.23
#Mann= 3 ,-1,0
       0      .1       0   181.6    .045       0   206.3      .1       0
Bank Sta=181.6,206.3
XS Rating Curve= 0 ,0
Exp/Cntr(USF)=0,0
Exp/Cntr=0.3,0.1

Type RM Length L Ch R = 1 ,4073    ,147.8,145.5,146.4
XS GIS Cut Line= 3
2182372.75555801488848.5655987262182493.88818659488835.814795717
2182703.21386931488697.681096458
#Sta/Elev= 30
       0 3180.15    15.5 3173.58    23.5 3171.48    35.6  3165.3    51.7  3160.2
    64.4 3153.76    83.9  3146.9    97.2 3139.09     112 3127.62   116.1 3126.14
   133.8 3124.07   139.8 3121.09   143.7 3119.82   148.5 3120.05   153.23119.468
   162.8 3118.47   172.5 3119.33   182.1 3121.77   194.6 3127.35   201.2 3129.55
   214.9 3131.01     230 3135.29   273.1 3134.95   286.4 3136.75   301.9 3142.73
     313 3152.07   329.9 3162.49   335.4  3164.1   344.8 3169.62   372.6 3182.77
#Mann= 3 ,-1,0
       0      .1       0   153.2    .045       0   172.5      .1       0
Bank Sta=153.2,172.5
XS Rating Curve= 0 ,0
Exp/Cntr(USF)=0,0
Exp/Cntr=0.3,0.1

Type RM Length L Ch R = 1 ,3928    ,126,130.8,139.1
XS GIS Cut Line= 3
2182397.13684426488978.1332808052182540.33104855 488984.16251046
2182807.12446074488774.646779978
#Sta/Elev= 30
       0 3191.88     9.7 3185.55    19.1 3177.87    43.1 3164.94    63.1 3158.17
    75.1 3151.91    95.1  3143.5   111.1 3137.95   131.2 3133.19   143.3 3128.06
   163.5 3122.32   168.6 3121.72   188.9 3124.08   199.1 3123.99   204.2 3122.01
   212.9 3116.81   229.6 3116.15   251.8 3112.65     265 3109.58   270.3  3109.4
   287.8 3109.53   295.7 3110.06   305.9 3114.26   347.6 3144.46   366.9 3155.09
   374.8 3160.52   427.4 3180.93   453.4 3191.57   464.4  3196.9   482.5 3203.86
#Mann= 3 ,-1,0
       0      .1       0     265    .045       0   287.8      .1       0
Bank Sta=265,287.8
XS Rating Curve= 0 ,0
Exp/Cntr(USF)=0,0
Exp/Cntr=0.3,0.1

Type RM Length L Ch R = 1 ,3797    ,174,174.7,175.3
XS GIS Cut Line= 3
2182406.66945728489026.1831307552182574.15634294489021.575531296
 2182866.6162974488975.047811268
#Sta/Elev= 30
       0 3197.52    13.5 3188.96    25.5 3175.69    41.5 3166.51    53.5 3156.96
    57.5 3154.98    77.5 3145.47   101.5 3138.18   113.5 3135.92   125.6 3130.75
   145.6 3124.75   161.6 3117.78   193.9 3118.28   214.1 3116.16   222.2 3110.97
   226.3 3109.82   253.5 3110.76   270.9 3107.91   287.1 3110.12   305.9 3106.69
   323.6 3105.22   335.7 3104.66   341.33105.166   355.9 3114.45   388.3 3143.05
   400.7 3153.09     420 3165.44   432.9 3177.55   449.2 3187.46   463.7 3194.47
#Mann= 3 ,-1,0
       0      .1       0   323.6    .045       0   341.3      .1       0
#XS Ineff= 2 , 0
          287.96 3125.47
Permanent Ineff=
       F       F
Bank Sta=323.6,341.3
XS Rating Curve= 0 ,0
Exp/Cntr(USF)=0,0
Exp/Cntr=0.3,0.1

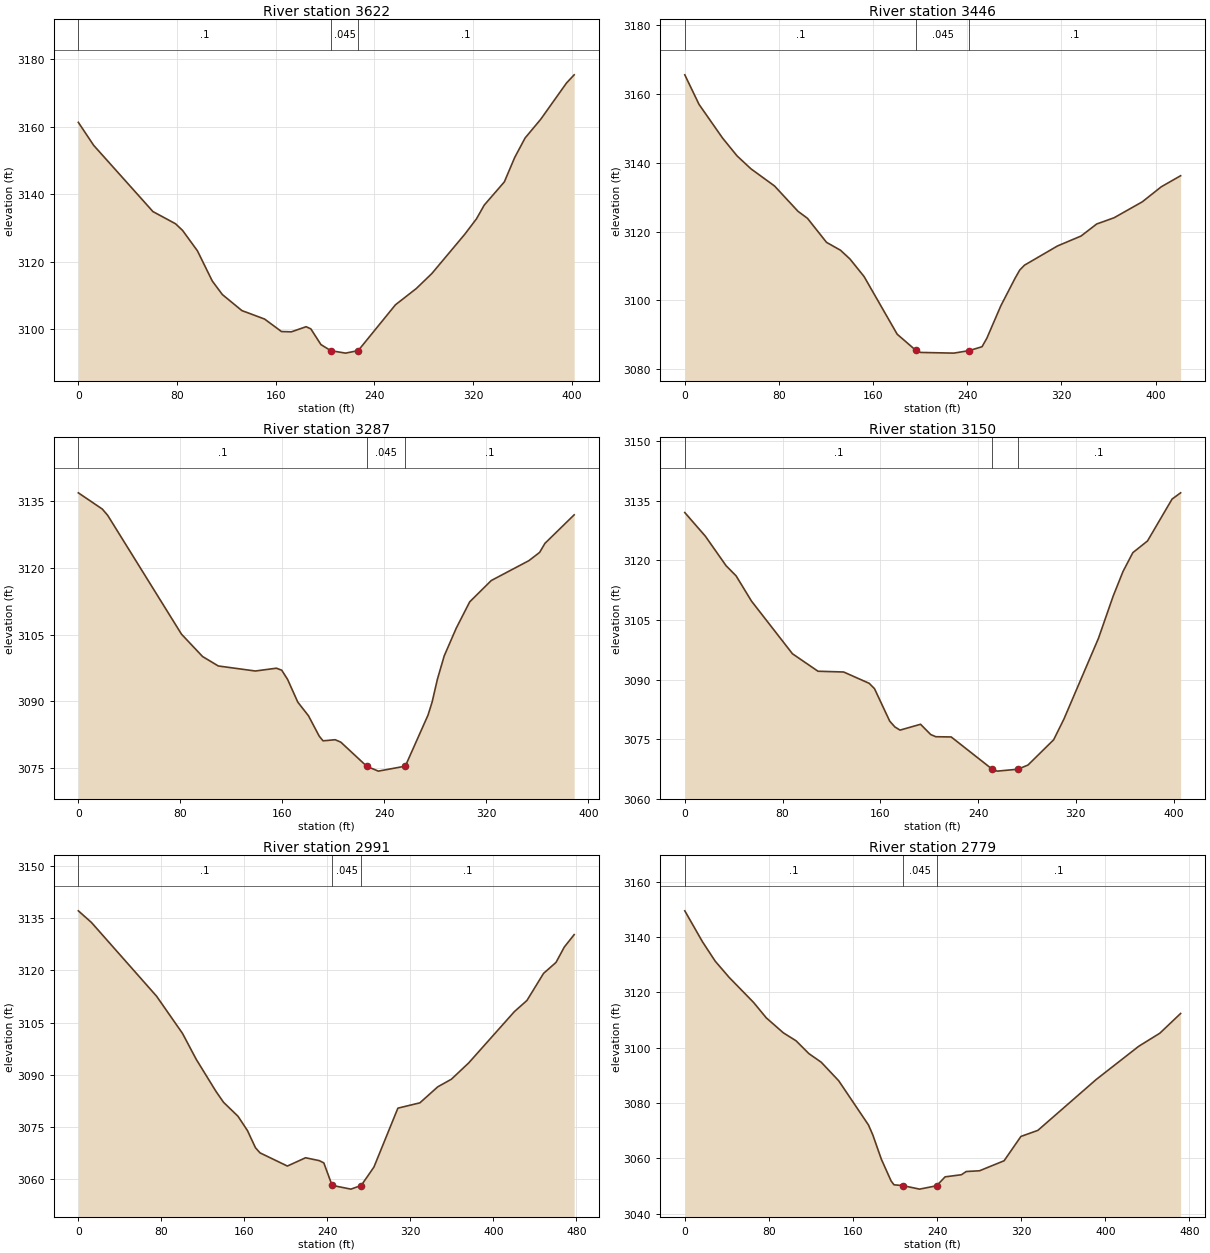
Type RM Length L Ch R = 1 ,3622    ,177.1,176.3,175.7
XS GIS Cut Line= 3
2182491.76305275489175.8362092792182741.46627834489162.022839354
 2182885.9753791489115.269894989
#Sta/Elev= 30
       0  3161.3    12.4  3154.5    60.5 3134.85    78.8 3131.24    84.5 3129.28
    96.6  3123.2   108.6 3114.27   116.8 3110.25   132.6 3105.51     151    3103
   164.7  3099.3   172.7 3099.21   184.7 3100.73   188.5 3100.09   196.7 3095.43
   204.7 3093.63   216.7  3092.9   226.9 3093.65   257.1 3107.22     274 3112.04
   286.6 3116.48   313.3 3128.12   322.8  3132.7   329.1 3136.77   345.4 3143.65
   353.8 3150.89   362.2 3156.65   374.9 3162.21   395.8 3172.96     402 3175.38
#Mann= 3 ,-1,0
       0      .1       0   204.7    .045       0   226.9      .1       0
Bank Sta=204.7,226.9
XS Rating Curve= 0 ,0
Exp/Cntr(USF)=0,0
Exp/Cntr=0.3,0.1

Type RM Length L Ch R = 1 ,3446    ,165,158.9,148.5
XS GIS Cut Line= 2
2182492.09721131489351.9455193622182912.63597969489327.828600746
#Sta/Elev= 30
       0 3165.64    12.1 3157.04    32.1 3147.24    44.4 3142.06    56.2  3138.3
    76.2 3133.32    96.2 3125.93   104.2 3123.91   120.4 3116.91   132.3 3114.61
   140.3 3112.07   152.3 3106.97   180.4  3090.2   196.4 3085.46   200.4 3084.89
   228.5 3084.69   241.4 3085.41   252.5 3086.55   256.6 3089.03   268.5 3098.48
   280.5 3106.43   284.5 3108.84   288.6 3110.28   316.6 3115.86   336.6 3118.75
   349.9 3122.25   364.7 3124.07   388.7 3128.71   404.7 3133.06   421.2 3136.29
#Mann= 3 ,-1,0
       0      .1       0   196.4    .045       0   241.4      .1       0
Bank Sta=196.4,241.4
XS Rating Curve= 0 ,0
Exp/Cntr(USF)=0,0
Exp/Cntr=0.3,0.1

Type RM Length L Ch R = 1 ,3287    ,126.9,136.9,147.6
XS GIS Cut Line= 3
2182545.95396554 489463.791843892182703.21386931489505.231953668
2182917.85238662489434.039970203
#Sta/Elev= 30
       0  3136.9    18.8 3133.25      23 3131.85    80.9 3105.12    97.4  3100.1
   109.8 3097.97   138.8 3096.84   155.3 3097.47   159.5 3097.02   164.1 3094.95
   172.1 3089.84   180.5 3086.76   188.9 3082.19   191.9 3081.14   201.4 3081.39
   205.8 3080.85   226.3 3075.39   235.3 3074.33   256.4 3075.45   274.2 3086.92
   277.4 3089.84   281.6 3095.03   286.9 3100.23   296.3 3106.45   306.9 3112.39
   323.8 3117.18   353.3 3121.65   361.7  3123.5   365.9 3125.54   388.8 3131.95
#Mann= 3 ,-1,0
       0      .1       0   226.3    .045       0   256.4      .1       0
Bank Sta=226.3,256.4
XS Rating Curve= 0 ,0
Exp/Cntr(USF)=0,0
Exp/Cntr=0.3,0.1

Type RM Length L Ch R = 1 ,3150    ,157.5,159.2,161
XS GIS Cut Line= 3
2182548.07909937489534.9838273542182847.72297008489628.489716084
2182939.10372497489619.989180745
#Sta/Elev= 30
       0 3131.99    16.9 3126.02    33.8 3118.62      42 3116.07    54.6 3109.72
    88.1 3096.49     109  3092.1     130 3091.91   150.9 3089.06   155.2 3087.73
   167.7 3079.54   171.9  3078.1   176.1  3077.3   192.9 3078.77   201.2 3076.19
   205.4 3075.64     218 3075.58   251.5 3067.49   255.7 3066.99   272.5 3067.47
   280.8 3068.52   301.8 3074.87   310.2 3080.07   338.5  3100.4   350.4  3110.9
   358.5 3117.14   366.6 3121.91   378.6 3124.85   398.7 3135.38   405.7 3136.95
#Mann= 3 ,-1,0
       0      .1       0   251.5    .045       0   272.5      .1       0
Bank Sta=251.5,272.5
XS Rating Curve= 0 ,0
Exp/Cntr(USF)=0,0
Exp/Cntr=0.3,0.1

Type RM Length L Ch R = 1 ,2991    ,221.9,211.9,207
XS GIS Cut Line= 3
2182492.70013428489648.8850798292182827.77457231489800.821667113
2182937.65728276 489804.89139713
#Sta/Elev= 30
       0 3137.11    12.6 3133.78    75.4 3112.59   100.4  3101.9   113.6 3094.47
   132.8 3085.18     140 3082.09   153.9 3078.09     163 3073.99   170.7 3069.07
   175.1 3067.58   201.5 3063.79     219 3066.17   232.2 3065.35   236.6  3064.7
   244.6 3058.24   262.7 3057.16  272.63  3058.2   284.9 3063.49     308 3080.42
   329.2 3081.95   346.4 3086.54   359.6 3088.74   376.3 3093.43   420.3 3108.16
   432.4 3111.36   448.4 3119.14   460.4 3122.29   468.4  3126.7   477.9 3130.27
#Mann= 3 ,-1,0
       0      .1       0   244.6    .045       0  272.63      .1       0
Bank Sta=244.6,272.63
XS Rating Curve= 0 ,0
Exp/Cntr(USF)=0,0
Exp/Cntr=0.3,0.1

Type RM Length L Ch R = 1 ,2779    ,135,139.4,141.8
XS GIS Cut Line= 3
2182411.57850476489905.5178460552182668.69804015489945.881413176
2182880.03039181489943.829224596
#Sta/Elev= 30
       0 3149.48    16.8 3138.31    28.9  3131.3    42.2 3125.42    65.4 3116.38
    77.5  3110.8    93.7  3105.4   105.9 3102.49     118 3097.88   129.7 3094.79
   146.4 3088.06   174.7 3072.09   178.8 3068.53   186.9 3059.76   196.2 3051.88
     199 3050.47   207.7 3050.15   223.3  3048.9   239.5 3050.12   247.6 3053.34
   263.1  3054.1   267.7 3055.27   280.3 3055.53   303.7 3059.15   319.7 3067.94
   335.8 3070.13   391.2 3088.49   431.8 3100.54   451.8 3105.24   471.6 3112.38
#Mann= 3 ,0,0
       0      .1       0   207.7    .045       0   239.5      .1       0
Bank Sta=207.7,239.5
XS Rating Curve= 0 ,0
Exp/Cntr(USF)=0,0
Exp/Cntr=0.3,0.1