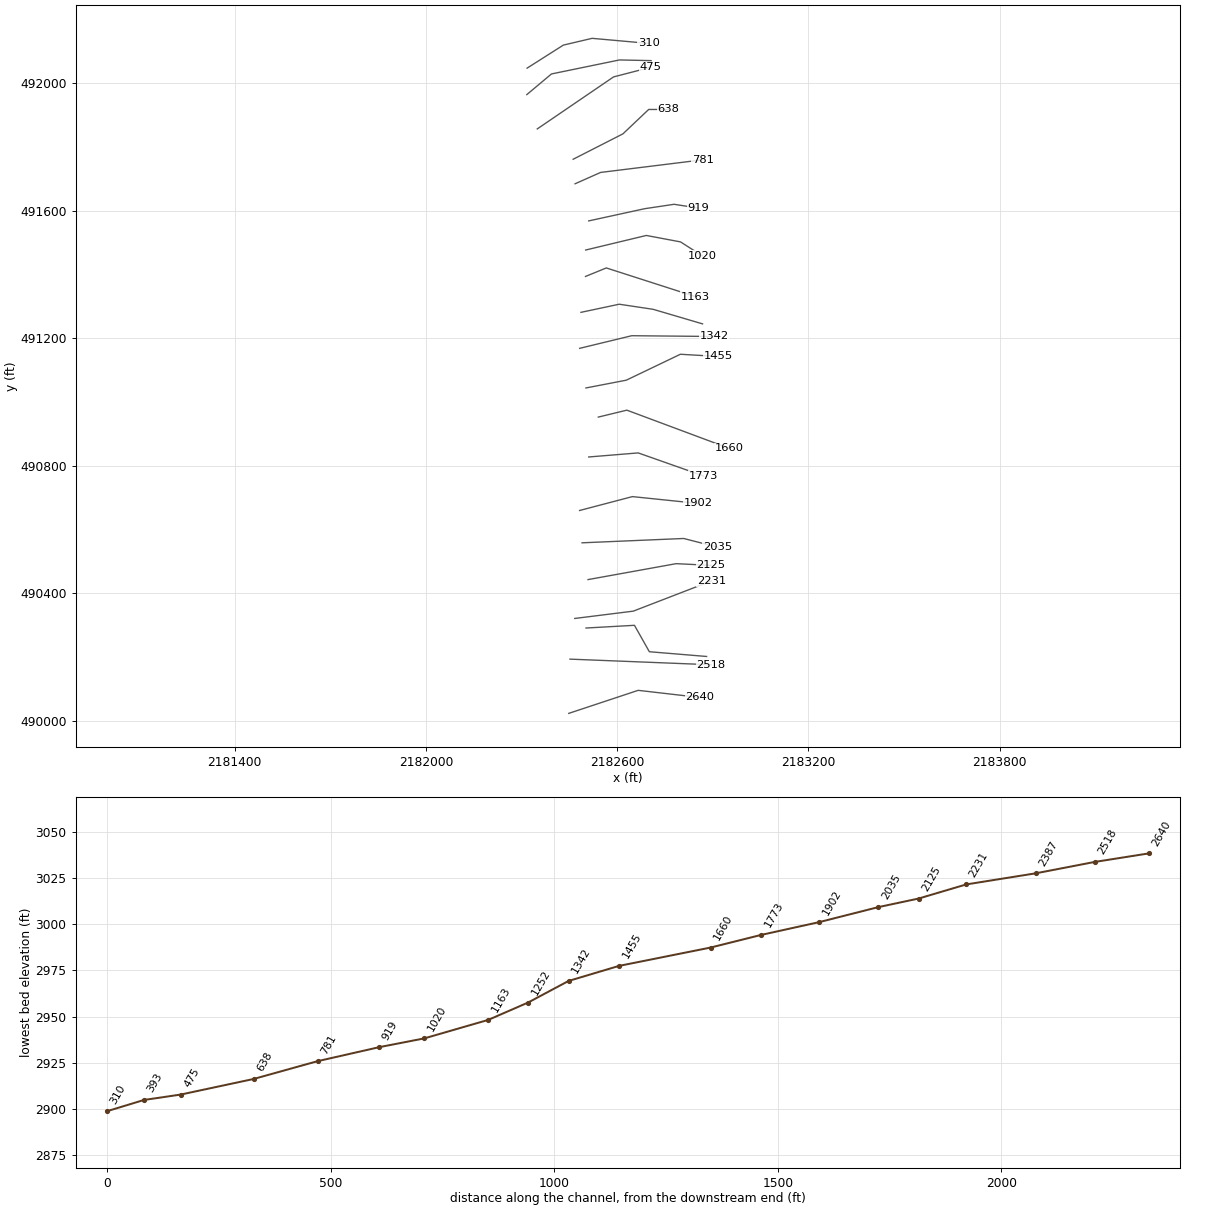
HEC-RAS study KENSCK.prj: KENSCK

--- KENSCK.g01 (geometry) --- (continued)

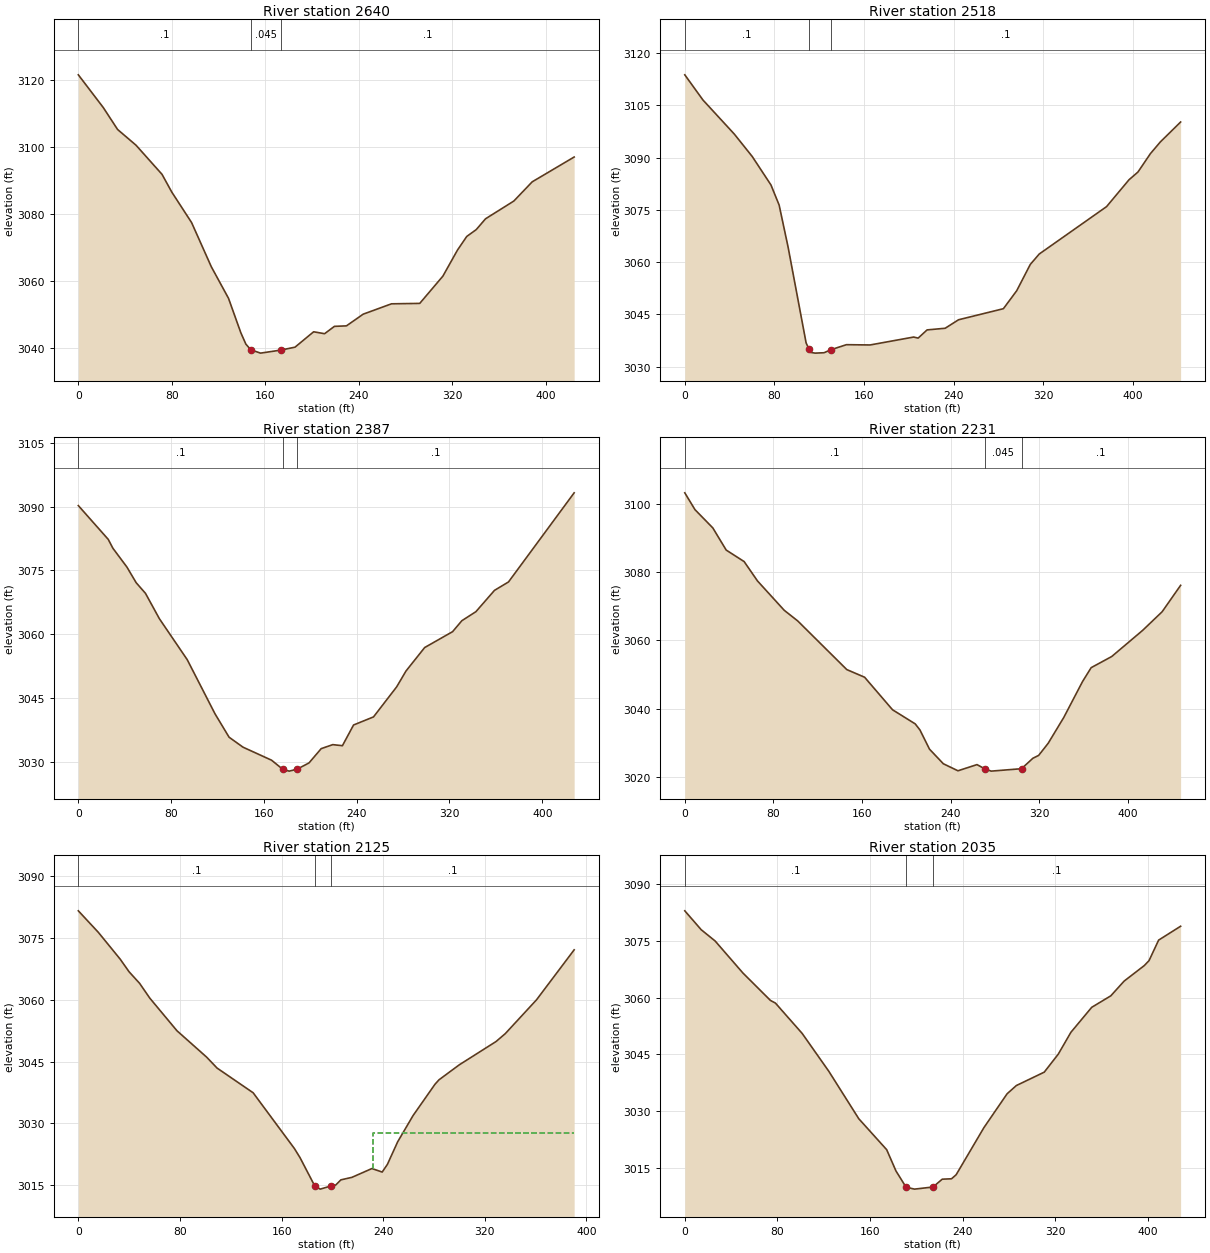
Type RM Length L Ch R = 1 ,2640    ,126.3,121.3,115.4
XS GIS Cut Line= 3
2182448.19780914490022.702042433 2182666.0240272490094.956592815
2182859.41120617 490072.64268755
#Sta/Elev= 30
       0 3121.65    21.3  3111.9    33.6 3105.33    49.4 3100.62    71.6 3091.94
      80 3086.62    96.9 3077.54   113.8 3064.33   128.5 3054.92     139 3044.67
   143.3 3041.27   147.5 3039.56   155.9 3038.56     173 3039.45   185.4 3040.34
   201.3 3044.93   210.7 3044.36   219.1 3046.55   229.4  3046.7   243.7 3050.19
   267.9 3053.28   292.1 3053.41   311.9 3061.55   324.3 3069.28   332.3 3073.39
   340.4 3075.43   348.4 3078.67   372.6 3083.97   388.3  3089.7   424.2 3097.11
#Mann= 3 ,-1,0
       0      .1       0   147.5    .045       0     173      .1       0
Bank Sta=147.5,173
XS Rating Curve= 0 ,0
Exp/Cntr(USF)=0,0
Exp/Cntr=0.3,0.1

Type RM Length L Ch R = 1 ,2518    ,143.9,131,115.2
XS GIS Cut Line= 2
2182452.00283411490192.8723253742182894.24682925490175.236828636
#Sta/Elev= 30
       0 3113.71    16.2 3106.49    44.2 3096.72    60.2 3090.29    76.9 3082.14
    84.2 3076.38    92.2 3064.34   108.3 3036.83   110.7 3035.16   112.3 3034.12
   116.3 3033.91   124.3 3034.02   130.8 3034.93   144.3 3036.33   165.4 3036.25
   204.3 3038.52   208.3 3038.22   216.3 3040.57   232.4 3041.04   244.4 3043.48
   284.4 3046.65   296.3 3051.81   308.4 3059.34   316.4 3062.33   376.5 3075.92
   396.5 3083.61   404.5 3085.83   415.6  3091.1   424.5 3094.47   442.6 3100.18
#Mann= 3 ,-1,0
       0      .1       0   110.7    .045       0   130.8      .1       0
Bank Sta=110.7,130.8
XS Rating Curve= 0 ,0
Exp/Cntr(USF)=0,0
Exp/Cntr=0.3,0.1

Type RM Length L Ch R = 1 ,2387    ,130.1,155.8,183.2
XS GIS Cut Line= 4
2182502.38872193490290.4689056132182654.33579111490298.969440952
2182701.08873548490216.0892213962182880.66254452490201.213284553
#Sta/Elev= 30
       0 3090.22    25.8 3082.27    29.8 3080.19    41.9 3075.76    49.9 3072.07
    57.9 3069.58    69.9 3063.61    93.9 3053.98   117.8 3041.27     130 3035.74
     142  3033.4   166.6 3030.34   176.33028.195   181.8 3027.77   188.5 3028.21
   198.9  3029.7   209.4 3033.06   219.4    3034   227.7 3033.75   237.3 3038.62
   254.5 3040.52   274.5  3047.6   282.5 3051.31   298.6 3056.83   322.7 3060.57
   330.7 3063.15   342.8 3065.27   358.8 3070.28   370.9 3072.26   427.5 3093.22
#Mann= 3 ,-1,0
       0      .1       0   176.3    .045       0   188.5      .1       0
Bank Sta=176.3,188.5
XS Rating Curve= 0 ,0
Exp/Cntr(USF)=0,0
Exp/Cntr=0.3,0.1

Type RM Length L Ch R = 1 ,2231    ,109.5,106.6,107.6
XS GIS Cut Line= 3
2182467.02427783490320.4525128362182650.58255071490343.397296946
2182895.80493089  490438.0445314
#Sta/Elev= 30
       0  3103.2     9.2 3098.27    25.3 3092.93    37.4 3086.44    53.6 3083.07
    65.7 3077.38    89.8 3068.81     102 3065.69   146.3 3051.45   162.4 3049.21
   187.6 3039.69   208.1 3035.55   212.4 3033.76     221 3028.15   233.5 3023.88
   246.7 3021.82   263.9 3023.63   271.1 3022.37   276.7 3021.72  304.13 3022.43
   314.4 3025.49   319.6 3026.33   328.2 3029.88   342.3 3037.45   359.2 3047.94
     367 3052.01   385.6 3055.28   413.4  3062.9   431.1 3068.38   447.8 3076.12
#Mann= 3 ,-1,0
       0      .1       0   271.1    .045       0  304.13      .1       0
Bank Sta=271.1,304.13
XS Rating Curve= 0 ,0
Exp/Cntr(USF)=0,0
Exp/Cntr=0.3,0.1

Type RM Length L Ch R = 1 ,2125    ,92,89.8,88.9
XS GIS Cut Line= 3
2182508.76412343490442.4159747982182785.03152195490492.356619915
2182894.47591444490487.043785328
#Sta/Elev= 30
       0 3081.54    15.7 3076.34    32.9 3069.84      40 3066.74    48.2 3063.97
    56.3 3060.35    77.6 3052.47     101 3046.06   109.2 3043.41   137.6 3037.42
   170.1 3023.89   174.5 3021.69  186.09 3014.83   190.4 3014.05   198.6 3014.79
   202.6 3015.04   206.7  3016.3   215.3  3016.9   231.1 3019.04   239.2 3018.19
   243.3 3020.06   251.4 3025.54   263.5 3031.89   280.7 3039.46   283.9 3040.56
   299.9  3044.2   328.8 3049.84     336 3051.73   360.7 3059.97   390.3 3072.08
#Mann= 3 ,-1,0
       0      .1       0  186.09    .045       0   198.6      .1       0
#XS Ineff= 2 , 0
                          231.67         3027.62
Permanent Ineff=
       F       F
Bank Sta=186.09,198.6
XS Rating Curve= 0 ,0
Exp/Cntr(USF)=0,0
Exp/Cntr=0.3,0.1

Type RM Length L Ch R = 1 ,2035    ,134.3,132.6,130.5
XS GIS Cut Line= 3
2182489.98698094490557.791450191 2182808.7824989490571.357216913
2182914.59547933490544.225683469
#Sta/Elev= 30
       0 3082.95    14.2 3077.95    26.2 3074.98    50.2 3066.52      74 3059.27
    78.3 3058.57   101.4 3050.55   124.4 3040.55   150.3 3028.01   174.4 3019.83
   182.4 3014.22   191.1 3009.93   198.4 3009.41   214.4 3009.97   222.4 3012.04
   230.4 3012.14   234.4 3013.21   258.4 3025.67   278.4  3034.6   286.4 3036.78
   310.5 3040.32   322.6 3045.07   333.5 3050.84   351.5 3057.45     368 3060.49
   379.5 3064.38   396.9 3068.48     401 3069.78   409.3 3075.21   428.3 3078.88
#Mann= 3 ,-1,0
       0      .1       0   191.1    .045       0   214.4      .1       0
Bank Sta=191.1,214.4
XS Rating Curve= 0 ,0
Exp/Cntr(USF)=0,0
Exp/Cntr=0.3,0.1

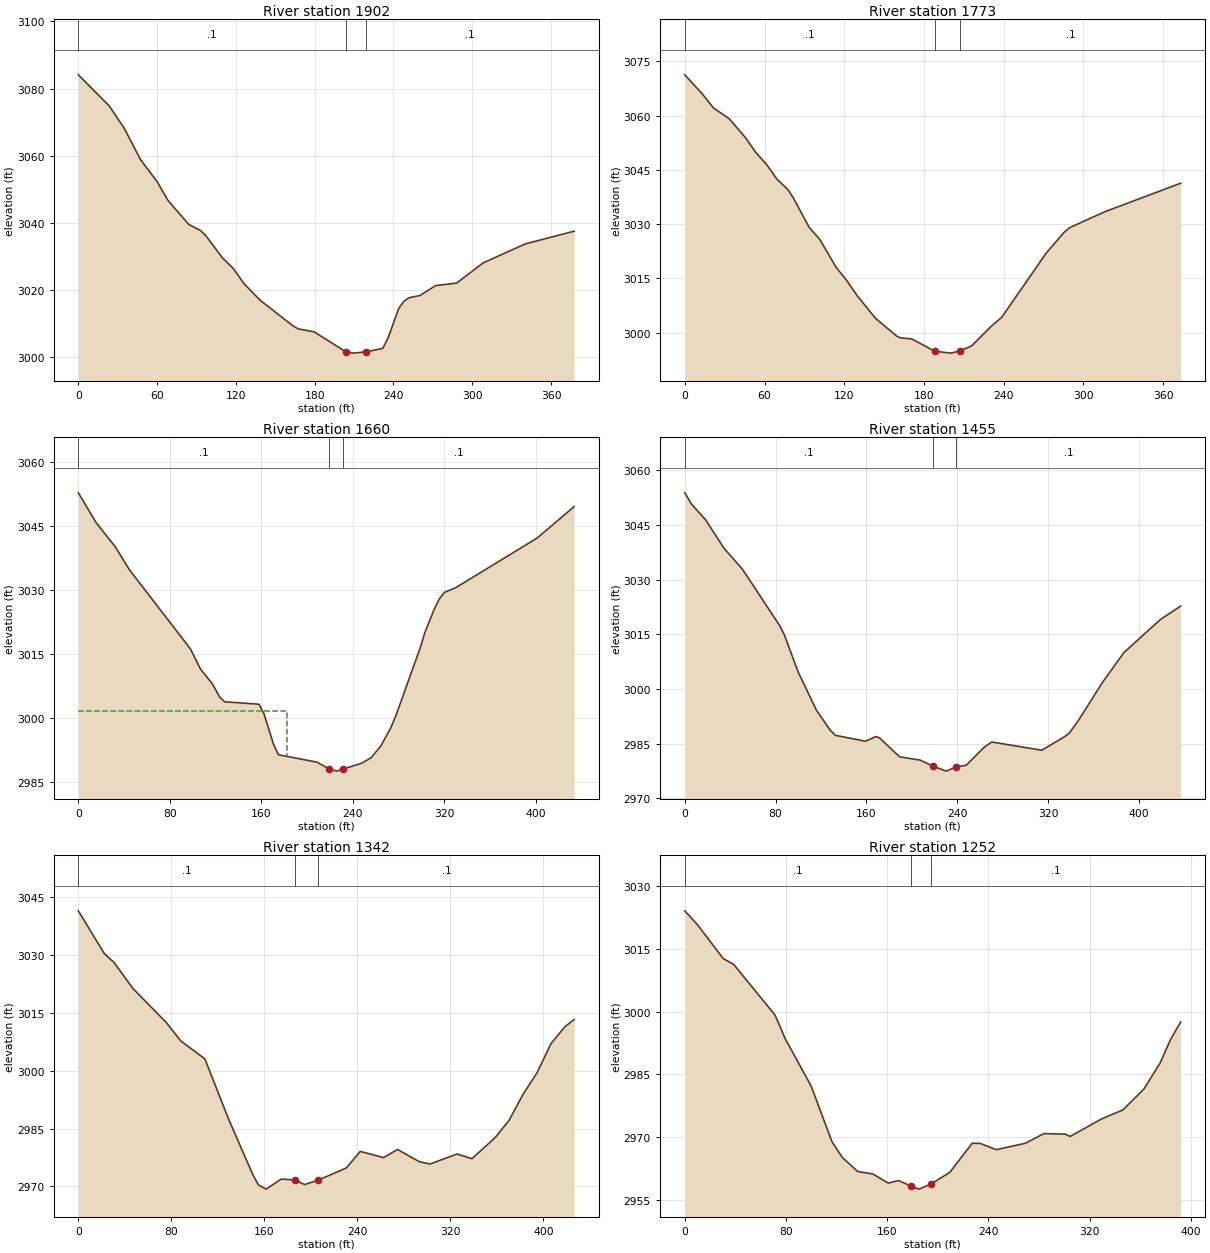
Type RM Length L Ch R = 1 ,1902    ,133.4,129.3,126.8
XS GIS Cut Line= 3
 2182482.1999505490659.1796259442182647.96038961490702.744869557
2182853.03580466490681.493531209
#Sta/Elev= 30
       0  3084.1    23.6 3074.82    35.1 3068.09    47.5 3058.76    59.9 3052.37
    68.2 3046.75    84.1 3039.56      93 3037.77    97.2 3036.17   109.6 3029.67
   117.8 3026.53   126.1 3021.95   138.5 3016.97   163.3 3009.41   167.5 3008.46
   179.6 3007.58   203.8 3001.61   209.4 3001.24   219.2 3001.62   231.9 3002.67
   235.9 3005.77     244 3014.53     248 3016.73     252 3017.75   260.1 3018.39
   272.1 3021.34   288.2 3022.11   308.3 3028.11   340.5 3033.78   377.6 3037.54
#Mann= 3 ,-1,0
       0      .1       0   203.8    .045       0   219.2      .1       0
Bank Sta=203.8,219.2
XS Rating Curve= 0 ,0
Exp/Cntr(USF)=0,0
Exp/Cntr=0.3,0.1

Type RM Length L Ch R = 1 ,1773    ,114.2,112.9,112.9
XS GIS Cut Line= 3
2182510.88925727 490827.06519889 2182666.0240272490839.816001899
2182871.09944226490767.561451517
#Sta/Elev= 30
       0 3071.27    13.3 3065.94    21.4 3062.17    33.4 3059.14    45.4 3054.01
    53.5 3049.78    61.5 3046.49    69.5 3042.36    77.8 3039.45    81.6  3037.3
    93.6  3029.1   101.6 3025.76   113.7 3018.15   121.7 3014.47   129.7 3010.21
   143.4 3003.99   159.4 2999.04   162.2 2998.54   170.7 2998.26   188.1 2994.84
   200.2 2994.32   207.2 2994.96   215.9 2996.33     230 3001.55   238.5 3004.24
   271.9 3021.95   285.2 3027.63   289.4 3028.98   316.2 3033.43   373.1  3041.3
#Mann= 3 ,-1,0
       0      .1       0   188.1    .045       0   207.2      .1       0
Bank Sta=188.1,207.2
XS Rating Curve= 0 ,0
Exp/Cntr(USF)=0,0
Exp/Cntr=0.3,0.1

Type RM Length L Ch R = 1 ,1660    ,195.4,205.6,215
XS GIS Cut Line= 3
2182540.92821597490952.2199340412182630.46227634490973.925160795
2182950.61437097490854.546413643
#Sta/Elev= 30
       0 3052.67    15.7 3045.63    32.2 3040.08    44.5 3034.72    98.2 3016.06
   106.8 3011.41   117.2 3007.95   123.8 3004.78   128.1 3003.71     158 3003.15
   162.3 3000.99   170.8 2993.74   175.1 2991.31   208.8 2989.57   219.72987.934
   226.3 2987.47   231.6 2987.97   247.6 2989.29   256.2 2990.62   264.7 2993.38
   273.3 2997.58   277.6 3000.29   298.9 3016.18   303.1 3019.87   311.6 3025.53
   315.9 3027.84   320.2 3029.32   330.4 3030.48   401.3 3042.06   433.8 3049.44
#Mann= 3 ,-1,0
       0      .1       0   219.7    .045       0   231.6      .1       0
#XS Ineff= 2 , 0
          182.55 3001.67
Permanent Ineff=
       F       F
Bank Sta=219.7,231.6
XS Rating Curve= 0 ,0
Exp/Cntr(USF)=0,0
Exp/Cntr=0.3,0.1

Type RM Length L Ch R = 1 ,1455    ,116.5,112.4,102.7
XS GIS Cut Line= 4
2182502.18698244491043.5965105872182628.79916926491067.989684194
2182798.38980481491149.3002628842182918.03251345491142.330784711
#Sta/Elev= 30
       0 3053.82     6.1 3050.64    18.3 3046.44    34.6 3038.59    50.9 3032.83
    83.5 3017.43    87.6 3014.94    99.8 3004.72   116.1 2994.12   128.3 2988.62
   132.7 2987.28   159.3 2985.66   168.3 2986.94   171.3 2986.65   189.3 2981.39
   207.3 2980.49   218.8 2978.84   230.3 2977.46   239.1  2978.6     248 2979.08
   264.3 2984.15   270.5 2985.45   314.6  2983.2   334.8 2986.94   338.8 2987.89
   346.9 2991.39     368 3001.78   386.9 3009.99     419 3019.03   436.9 3022.76
#Mann= 3 ,-1,0
       0      .1       0   218.8    .045       0   239.1      .1       0
Bank Sta=218.8,239.1
XS Rating Curve= 0 ,0
Exp/Cntr(USF)=0,0
Exp/Cntr=0.3,0.1

Type RM Length L Ch R = 1 ,1342    ,91.6,90.5,88.1
XS GIS Cut Line= 3
2182482.44012761491167.8855380132182645.83525577491207.464155313
2182904.09355711491205.056088271
#Sta/Elev= 30
       0 3041.42    22.4 3030.32    30.6 3028.08    47.1 3021.25    75.9 3012.39
    88.2 3007.67   108.8 3003.08   129.4 2987.32   149.9 2973.17   154.9 2970.38
   161.5 2969.31   174.5 2971.91 186.5052971.679   194.5 2970.49206.50492971.651
   230.5  2974.8   242.5 2979.09   262.5 2977.48   274.5 2979.58   293.3 2976.41
   302.5 2975.82   325.7 2978.42   338.5  2977.2   358.5 2982.67   370.5 2987.18
   382.5 2993.91   394.5 2999.46   406.5 3007.02   418.5 3011.41   426.4 3013.26
#Mann= 3 ,-1,0
       0      .1       0 186.505    .045       0206.5049      .1       0
Bank Sta=186.505,206.5049
XS Rating Curve= 0 ,0
Exp/Cntr(USF)=0,0
Exp/Cntr=0.3,0.1

Type RM Length L Ch R = 1 ,1252    ,90.4,89.2,86.5
XS GIS Cut Line= 4
2182486.45021817491280.7812726122182606.52027983491306.282878629
2182712.77697157491290.3443748692182867.91174151491244.653997421
#Sta/Elev= 30
       0  3024.1     9.9 3020.82    30.4 3012.68    38.6 3011.31    71.3  2999.2
    79.5 2993.47    99.9  2982.2   116.3 2968.94   124.4  2965.2   136.6 2961.81
   148.7 2961.21   160.8 2959.04   168.9 2959.64   178.52958.368   185.1 2957.59
   194.8 2958.85   209.4 2961.58   227.2 2968.56   233.5 2968.52   246.2 2967.02
   269.3 2968.56   283.8 2970.86   300.5 2970.75   304.6 2970.18   329.6  2974.4
   346.3 2976.52     363 2981.55   375.6  2987.7   383.9 2993.32   391.9 2997.54
#Mann= 3 ,-1,0
       0      .1       0   178.5    .045       0   194.8      .1       0
Bank Sta=178.5,194.8
XS Rating Curve= 0 ,0
Exp/Cntr(USF)=0,0
Exp/Cntr=0.3,0.1

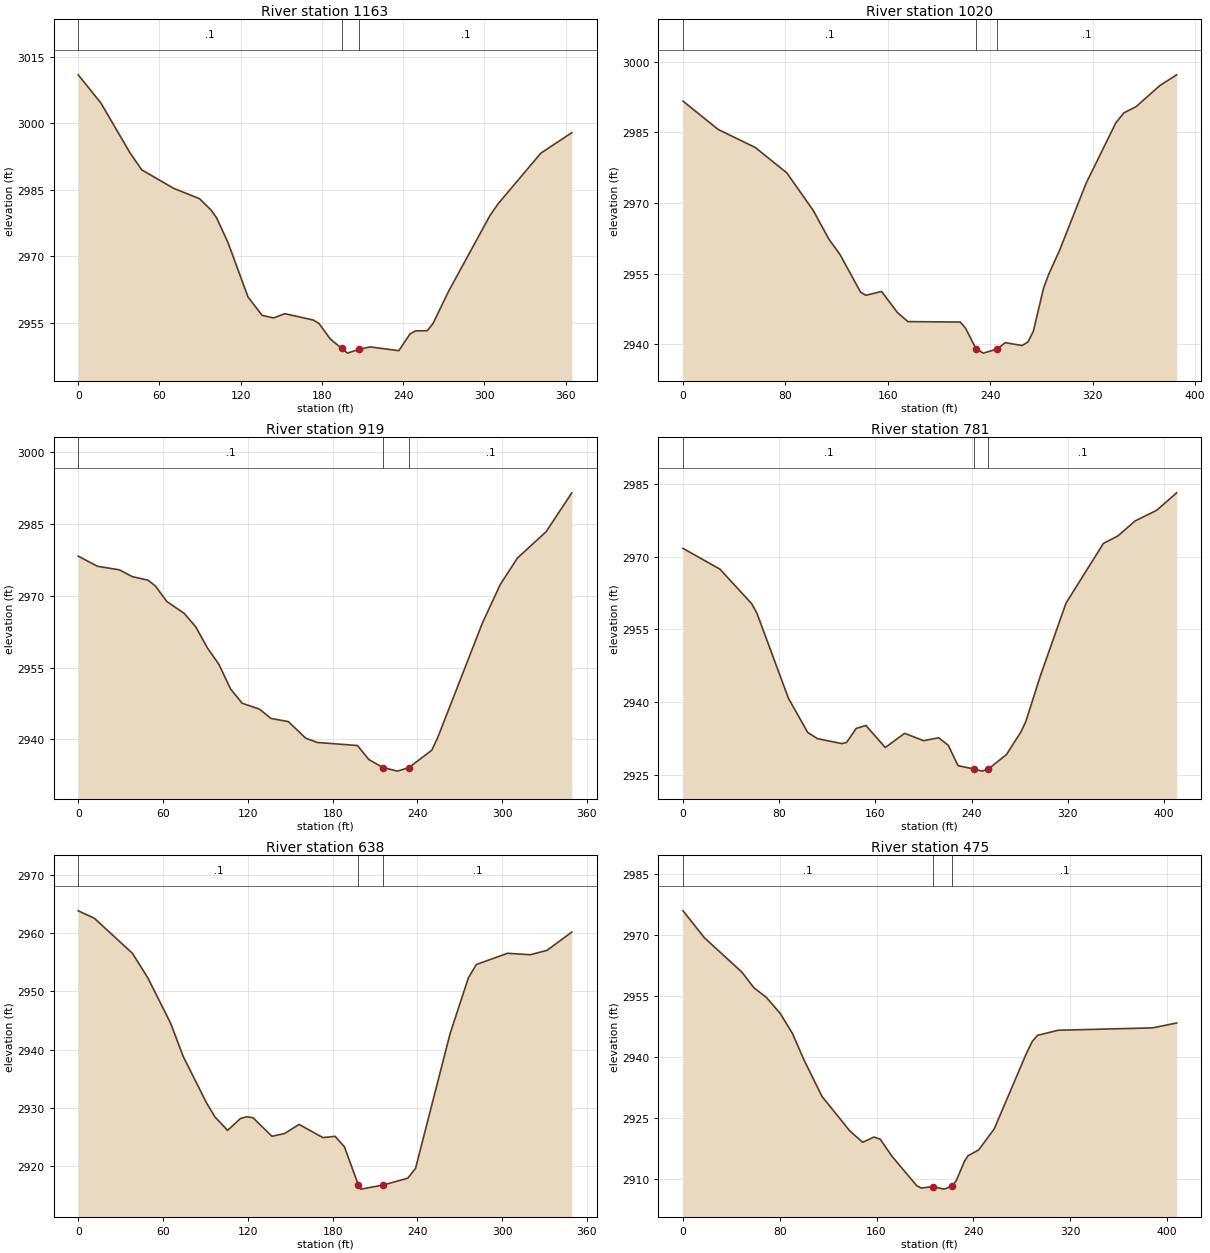
Type RM Length L Ch R = 1 ,1163    ,141.4,142.7,144.1
XS GIS Cut Line= 3
2182500.74599052491393.3952000722182566.01632053 491420.09669871
2182845.88758404491330.102758855
#Sta/Elev= 30
       0 3010.89    16.7 3004.56    38.3 2993.28    46.9 2989.47    70.5  2985.3
    89.6 2982.97      98 2980.44   102.2 2978.65   110.6 2973.08   125.4 2960.81
   135.8 2956.67   144.2 2956.09   152.6 2957.05   173.6 2955.62   177.8 2954.84
   186.2 2951.33   194.6 2949.23   198.8 2948.16   207.2    2949   215.6 2949.56
   236.7 2948.71   245.1 2952.52   249.3 2953.18   257.7 2953.21   261.9 2954.78
   273.7 2962.22   303.9 2979.09   309.8 2981.73   341.6 2993.23   364.5 2997.86
#Mann= 3 ,-1,0
       0      .1       0   194.6    .045       0   207.2      .1       0
Bank Sta=194.6,207.2
XS Rating Curve= 0 ,0
Exp/Cntr(USF)=0,0
Exp/Cntr=0.3,0.1

Type RM Length L Ch R = 1 ,1020    ,95.8,100.9,104.9
XS GIS Cut Line= 4
2182501.32615501 491476.293585412182691.52563322491521.983962858
2182798.84489188491501.7951914282182866.84917459491458.229947815
#Sta/Elev= 30
       0 2991.63    27.6  2985.6    56.4  2981.8    81.1  2976.4   101.7 2968.43
     114  2962.3   122.5 2959.13   138.7 2951.08   142.8 2950.42   155.1 2951.23
   167.5 2946.75   175.7 2944.83   216.6 2944.74   220.7 2943.43   228.8  2939.1
   234.5 2938.14   245.5 2939.01   251.7 2940.37   264.9 2939.75   269.5 2940.53
   273.6 2942.74   281.7 2952.01   285.8 2954.97     294 2959.87   314.9 2974.22
   338.1 2987.03   344.4 2989.15   353.9 2990.46   372.8 2995.01   385.6 2997.22
#Mann= 3 ,-1,0
       0      .1       0   228.8    .045       0   245.5      .1       0
Bank Sta=228.8,245.5
XS Rating Curve= 0 ,0
Exp/Cntr(USF)=0,0
Exp/Cntr=0.3,0.1

Type RM Length L Ch R = 1 ,919     ,135.7,137.8,135.9
XS GIS Cut Line= 4
2182510.88925727491567.6743403052182686.21279863491605.926749331
2182778.65612045491619.7401192572182854.09837158491608.051883166
#Sta/Elev= 30
       0 2978.27    13.6 2976.15    29.2  2975.4    38.2 2973.99    49.4 2973.24
    54.5 2972.07    62.7 2968.79      75 2966.31    83.2 2963.48    91.4 2959.11
    99.6 2955.64   107.8 2950.53     116 2947.54   128.2 2946.32   136.4 2944.37
   148.7  2943.7     161 2940.24   169.2 2939.35   197.6 2938.71   205.7 2935.77
   215.7  2934.1   225.9 2933.36     234  2934.1   250.2 2937.73   254.4 2940.37
     286 2964.28   298.7 2972.37   310.9  2977.9   331.1 2983.37   349.3 2991.49
#Mann= 3 ,-1,0
       0      .1       0   215.7    .045       0     234      .1       0
Bank Sta=215.7,234
XS Rating Curve= 0 ,0
Exp/Cntr(USF)=0,0
Exp/Cntr=0.3,0.1

Type RM Length L Ch R = 1 ,781     ,134.9,143.1,150
XS GIS Cut Line= 3
2182468.11082552491684.1448519142182548.21532144491719.746850099
 2182868.6333051491759.304625859
#Sta/Elev= 30
       0  2971.7    30.7 2967.42      57 2960.32    61.4 2958.36    87.7 2940.77
   103.7 2933.73   111.8 2932.46     132 2931.44     136 2931.66     144 2934.57
   152.1 2935.17   168.2 2930.63   184.3 2933.56   200.1 2932.04   212.6 2932.64
   220.6 2931.08   228.7 2926.89   242.3 2926.17   248.8 2925.76   253.9 2926.18
     269 2929.19   281.1 2933.89   285.1 2936.02   297.2 2945.44   318.5 2960.41
   349.6 2972.73   361.6 2974.26   375.9 2977.35   393.9 2979.56   410.5 2983.16
#Mann= 3 ,-1,0
       0      .1       0   242.3    .045       0   253.9      .1       0
Bank Sta=242.3,253.9
XS Rating Curve= 0 ,0
Exp/Cntr(USF)=0,0
Exp/Cntr=0.3,0.1

Type RM Length L Ch R = 1 ,638     ,164.6,163.1,160.7
XS GIS Cut Line= 4
2182462.01117907491761.0615192692182618.20851592491840.754038072
2182698.96360164491917.2588561242182761.65504977491917.258856124
#Sta/Elev= 30
       0 2963.81    11.4 2962.54    38.4 2956.52    49.3  2952.3    65.3 2944.58
    74.3 2938.84    90.9 2930.83    96.8 2928.46   105.7 2926.16   114.7 2928.18
   119.2  2928.5   123.7 2928.33   137.1 2925.15   146.1 2925.63   156.3 2927.19
   173.1 2924.93   181.8 2925.14   188.4 2923.34  198.28 2916.78   200.1 2916.09
   215.7 2916.79   233.2 2917.96   238.7 2919.65   263.2 2942.79   276.1 2952.32
   281.7  2954.6   303.8 2956.53   319.9 2956.28   331.8 2957.04   349.3 2960.17
#Mann= 3 ,-1,0
       0      .1       0  198.28    .045       0   215.7      .1       0
Bank Sta=198.28,215.7
XS Rating Curve= 0 ,0
Exp/Cntr(USF)=0,0
Exp/Cntr=0.3,0.1

Type RM Length L Ch R = 1 ,475     ,88.7,81.9,78.9
XS GIS Cut Line= 3
2182349.43749824491856.2211764742182588.76204159492019.397001487
 2182703.4795913492049.065333308
#Sta/Elev= 30
       0 2976.02    17.8 2969.36    48.7 2960.95    58.5 2957.15    68.9 2954.74
    80.4  2950.8    90.5 2945.86   100.1 2939.34   114.9 2930.41     138  2921.9
   148.6 2919.14   157.9 2920.42   163.1 2919.88   172.8 2915.69   193.4 2908.42
     197 2907.89     207 2908.23   215.7 2907.62  222.75 2908.36     226 2909.75
   232.9 2914.57   235.7 2915.82   244.5 2917.27   257.3  2922.4   284.1 2941.07
   288.9 2943.98   293.2 2945.42   310.3 2946.67   388.2 2947.25   408.2 2948.45
#Mann= 3 ,-1,0
       0      .1       0     207    .045       0  222.75      .1       0
Bank Sta=207,222.75
XS Rating Curve= 0 ,0
Exp/Cntr(USF)=0,0
Exp/Cntr=0.3,0.1

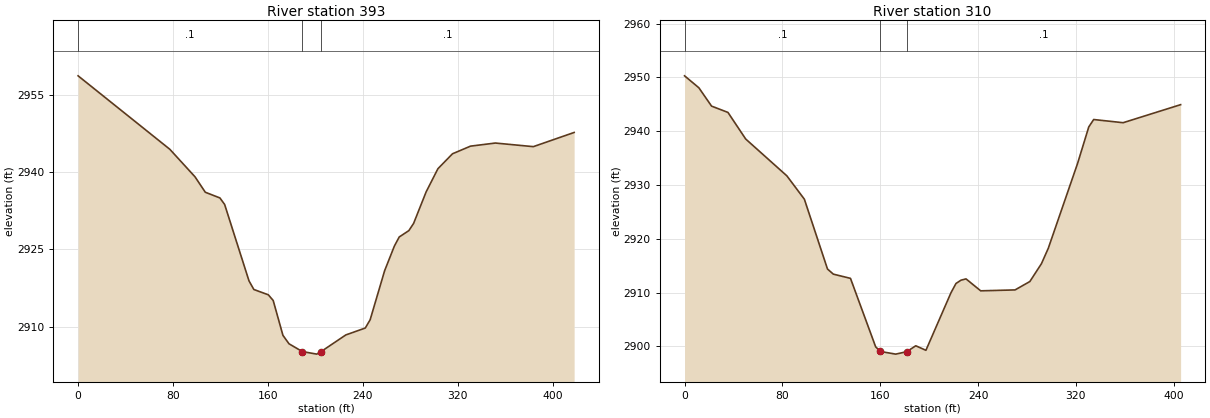
Type RM Length L Ch R = 1 ,393     ,82.4,82.9,82.9
XS GIS Cut Line= 4
2182316.65625482 491963.870373162182394.01746254492028.686520173
2182607.28349465492072.5942326652182706.59855862492070.503389213
#Sta/Elev= 30
       0 2958.65    77.3 2944.41    98.5 2939.08   107.2 2936.08   119.5 2934.98
   123.5 2933.71     144 2918.91   148.1 2917.23   160.3  2916.2   164.4  2915.1
   172.6 2908.35   177.7 2906.71   188.9  2905.2   201.1  2904.7   204.8  2905.2
   225.6 2908.42     242 2909.76   246.1 2911.36   258.3 2920.87   266.5 2925.64
   270.6 2927.41   278.7 2928.64   282.7 2930.03   293.3 2936.16   303.2 2940.64
   315.5 2943.54   330.7 2945.02   351.6 2945.62   383.6 2944.92     418 2947.67
#Mann= 3 ,-1,0
       0      .1       0   188.9    .045       0   204.8      .1       0
Bank Sta=188.9,204.8
XS Rating Curve= 0 ,0
Exp/Cntr(USF)=0,0
Exp/Cntr=0.3,0.1

Type RM Length L Ch R = 1 ,310     ,103.5,102,102.8
XS GIS Cut Line= 4
 2182317.5020783492046.8920200442182431.19673846492119.146570426
2182521.51492644492140.3979087742182698.96360164492124.459405013
#Sta/Elev= 30
       0 2950.29    11.7 2948.07    22.1 2944.66    35.5 2943.49      50 2938.55
    83.7  2931.7      98 2927.36   116.9 2914.39   121.7 2913.44   135.7 2912.66
   156.3 2899.93   160.2 2899.07   172.7 2898.58   181.7 2899.03   189.1 2900.13
   197.4 2899.29   217.9 2909.99     222 2911.71   226.1 2912.32   230.2 2912.56
   242.2 2910.34   270.3 2910.51   282.4 2912.07   291.9 2915.39   297.5 2918.26
   321.4 2933.99   330.6  2940.8   334.6 2942.17   358.7 2941.58   405.7 2944.93
#Mann= 3 ,-1,0
       0      .1       0   160.2    .045       0   181.7      .1       0
Bank Sta=160.2,181.7
XS Rating Curve= 0 ,0
Exp/Cntr(USF)=0,0
Exp/Cntr=0.3,0.1