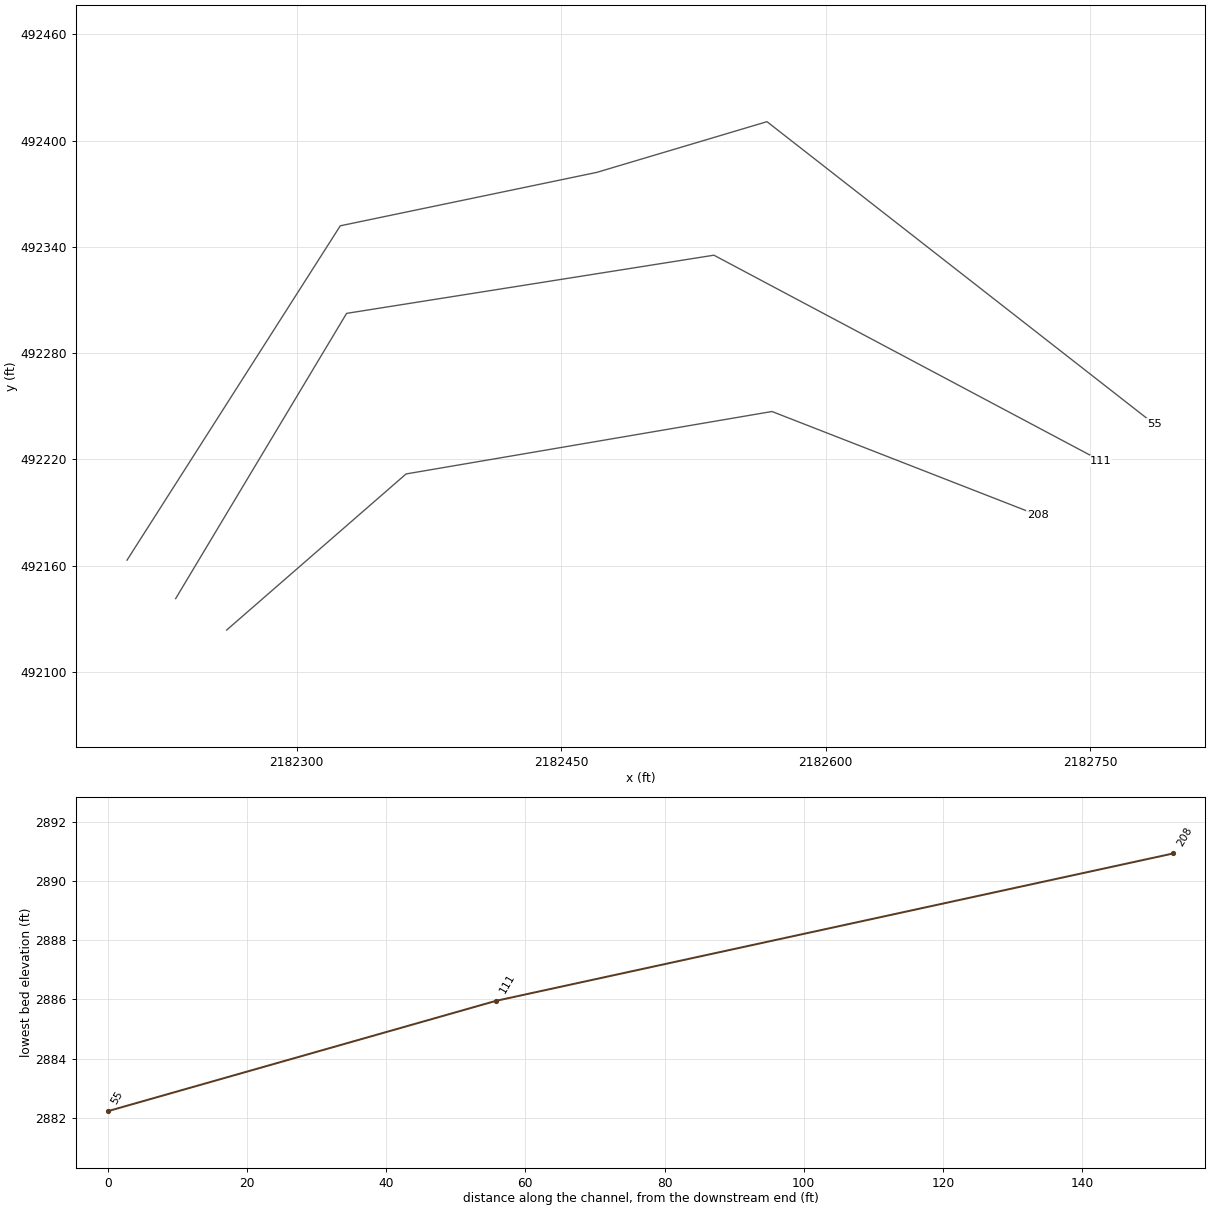
HEC-RAS study KENSCK.prj: KENSCK

--- KENSCK.g01 (geometry) --- (continued)

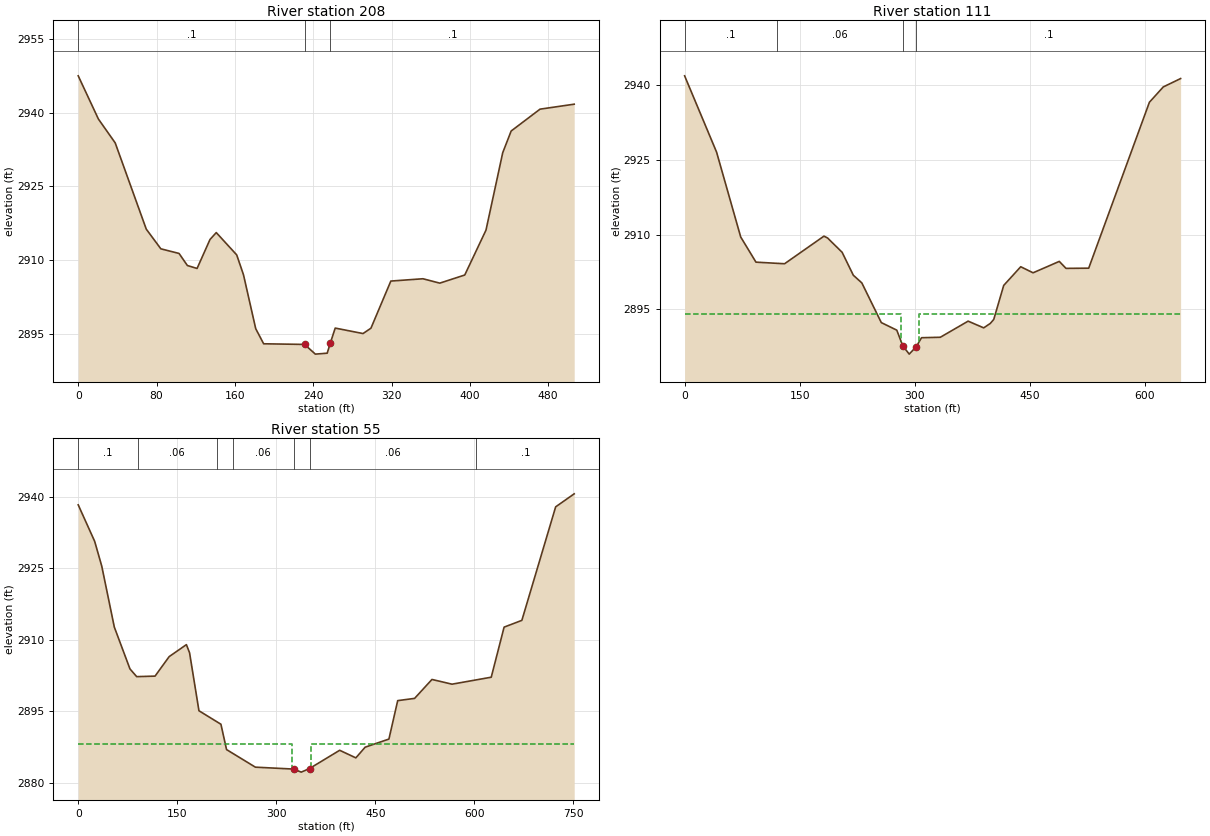
Type RM Length L Ch R = 1 ,208     ,95.7,97.3,97.7
XS GIS Cut Line= 4
2182260.37717555492123.6848309982182362.10988536492211.799776506
2182569.58052979492247.0457547082182720.17698211 492188.56947269
#Sta/Elev= 30
       0 2947.46    20.6 2938.69    37.8 2933.83    69.5 2916.32    84.4 2912.32
     103 2911.38   111.5 2908.93   121.4 2908.33   134.6 2914.21     141 2915.62
   161.9 2911.08   168.8 2907.06   181.3  2896.1   189.4 2893.03   231.2  2892.9
   242.2 2890.93   254.3 2891.12   257.6 2893.24   262.5 2896.22   290.9 2895.11
     299  2896.2   319.3 2905.77   352.1 2906.24   369.3 2905.35   394.8    2907
   416.5 2916.12   433.6 2931.85   442.2 2936.25   471.7 2940.69   506.6  2941.7
#Mann= 3 ,-1,0
       0      .1       0   231.2    .045       0   257.6      .1       0
Bank Sta=231.2,257.6
XS Rating Curve= 0 ,0
Exp/Cntr(USF)=0,0
Exp/Cntr=0.5,0.3

Type RM Length L Ch R = 1 ,111     ,55.8,55.8,55.8
XS GIS Cut Line= 4
2182231.46123618492141.4337570162182328.38767624492302.443793807
2182536.65936562492335.2866371322182756.14568443492219.135118054
#Sta/Elev= 30
       0  2941.9    41.7 2926.56    73.2 2909.49    93.1 2904.44   130.4 2904.12
   181.8 2909.67   186.5  2909.3   205.5 2906.42   220.1 2901.81   231.2 2900.27
   256.6 2892.29   276.8 2890.77   284.6 2887.63     293 2885.95   302.1 2887.43
   309.1 2889.25   333.6 2889.34   369.9 2892.58   390.2 2891.23   398.8 2892.12
   403.3 2892.92   416.3 2899.76   438.5 2903.52   454.6  2902.3   488.8 2904.59
   497.6 2903.19   527.2 2903.23   606.4 2936.59   624.5 2939.67   647.1 2941.35
#Mann= 4 ,-1,0
       0      .1       0     120     .06       0   284.6    .045       0
   302.1      .1       0
#XS Ineff= 2 , 0
           282.7    2894  305.98            2894
Permanent Ineff=
       F       F
Bank Sta=284.6,302.1
XS Rating Curve= 0 ,0
Exp/Cntr(USF)=0,0
Exp/Cntr=0.5,0.3

Type RM Length L Ch R = 1 ,55      ,,,
XS GIS Cut Line= 5
2182203.88173886492163.1381502892182324.81413457492351.883888163
 2182470.2526584492382.0404272182182566.75510536492410.661042668
2182786.24142417492240.038466368
#Sta/Elev= 30
       0 2938.26    24.9 2930.62    35.7 2925.39    54.7 2912.63    78.4 2903.86
    88.6 2902.24   116.4 2902.35   137.8 2906.44   163.9 2908.95   168.7 2907.24
   182.9 2895.09   216.2 2892.26   224.7 2886.95   268.4 2883.26   326.2 2882.86
   337.9 2882.22   350.5 2882.98   396.1  2886.8   420.6 2885.21   434.7 2887.45
   470.7 2889.15     484 2897.21   509.6 2897.68   535.9 2901.65   566.3 2900.66
   625.7 2902.12   645.2 2912.62   672.1 2914.04   723.3 2937.84   751.4 2940.57
#Mann= 7 ,-1,0
       0      .1       0      90     .06       0     210      .1       0
  234.16     .06       0   326.2    .045       0   350.5     .06       0
  603.35      .1       0
#XS Ineff= 2 , 0
          324.47 2888.15  352.14         2888.04
Permanent Ineff=
       F       F
Bank Sta=326.2,350.5
XS Rating Curve= 0 ,0
Exp/Cntr(USF)=0,0
Exp/Cntr=0.5,0.3
LCMann Table=0

Chan Stop Cuts=-1
Use User Specified Reach Order=0
Composite Channel Slope=5